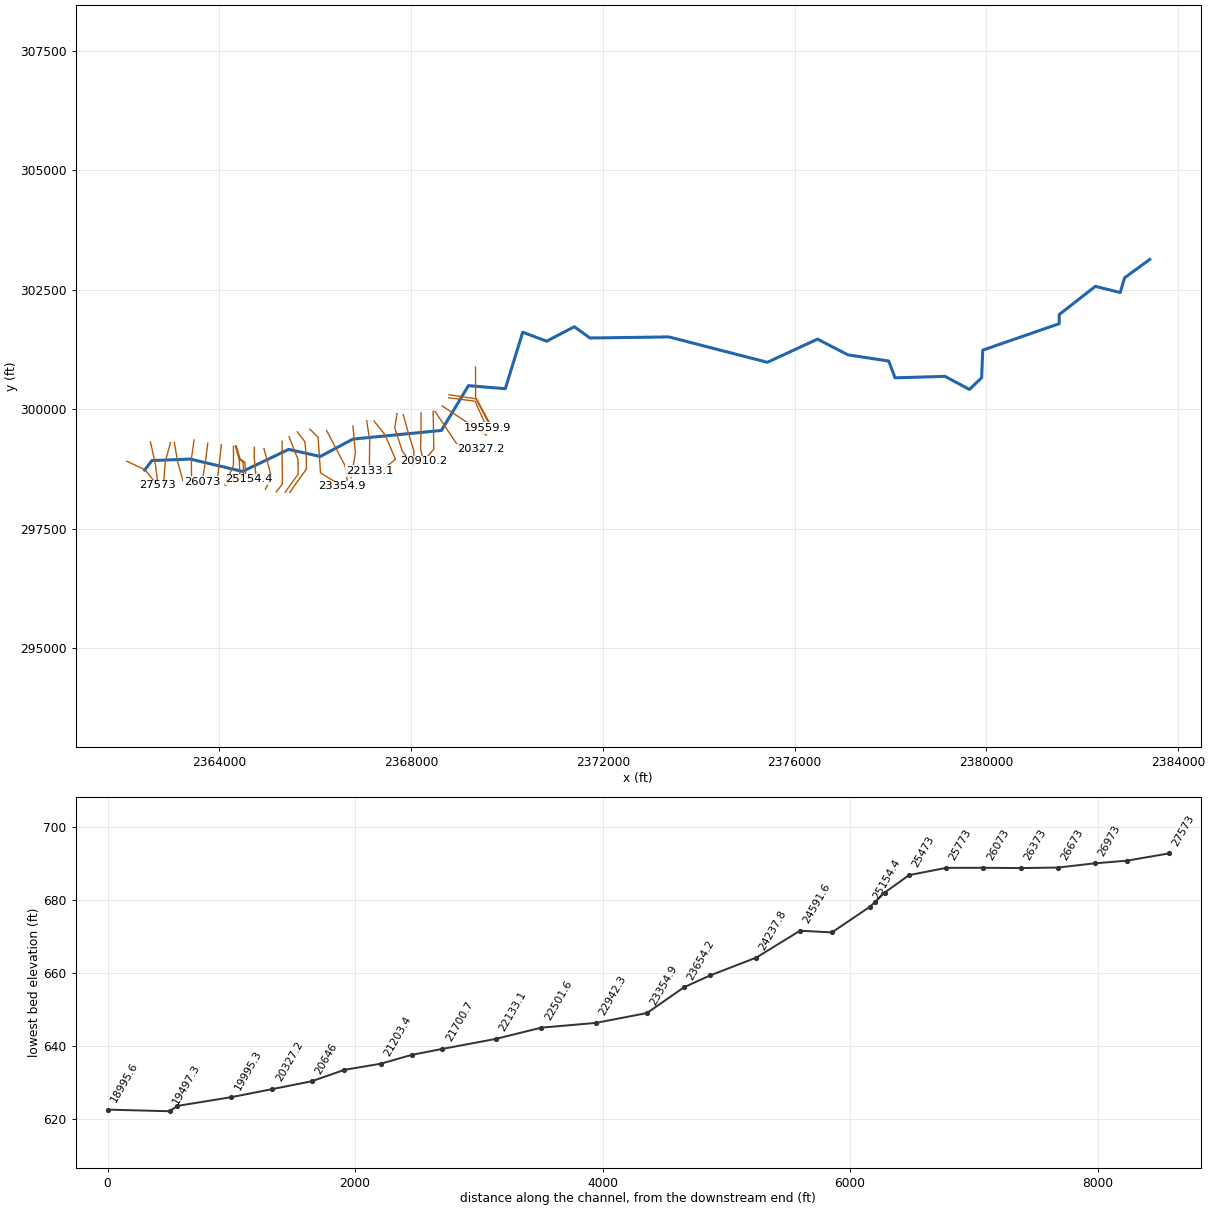
--- SYLVANRUN.prj (project) ---

Proj Title=SYLVANRUN
Current Plan=p01
Default Exp/Contr=0,0
English Units
Geom File=g01
Flow File=f01
Plan File=p01
BEGIN DESCRIPTION:
END DESCRIPTION:
DSS Export Rating Curves= 0
DSS Export Rating Curve Sorted= 0
DSS Export Volume Flow Curves= 0
DXF OffsetX= 0
DXF OffsetY= 0
DXF ScaleX= 0
DXF ScaleY= 0

--- SYLVANRUN.p01 (plan) ---

Plan Title=Floodplain
Program Version=4.00
Geom File=g01
Flow File=f01
K Sum by GR=0
Std Step Tol=0.01
Critical Tol=0.01
Num of Std Step Trials=20
Max Error Tol=0.3
Flow Tol Ratio=0.001
Split Flow NTrial=30
Split Flow Tol=0.02
Split Flow Ratio=0.02
Log Output Level=0
Friction Slope Method=1
Unsteady Friction Slope Method=2
Unsteady Bridges Friction Slope Method=1
Global Log Level=0
CheckData=False
Run HTab=0
Run UNet=0
Run PostProcess=0
UNET Theta=0
UNET Theta Warmup=0
UNET ZTol=0
UNET ZSATol=0
UNET MxIter=0
UNET MaxInSteps=0
UNET DtIC=0
UNET DtMin=0
UNET MaxCRTS=0
UNET WFStab=0
UNET SFStab=0
UNET WFX=0
UNET SFX=0
UNET DSS MLevel=0
UNET DZMax Abort=0
UNET Convert EG Bridges=0
UNET Use Existing IB Tables=0
UNET Froude Limit=0
UNET Froude Power=0
Write IC File=0
Echo Input=False
Echo Output=False
Write Detailed=0

--- SYLVANRUN.f01 (steady flow) ---

Flow Title=NFF Regression Equation
Program Version=4.00
Number of Profiles=1
Profile Names=P100yr
River Rch & RM=SYLVANRUN,Main      ,27573
977.0314
River Rch & RM=SYLVANRUN,Main      ,26073
1050.767
River Rch & RM=SYLVANRUN,Main      ,22501.6
1148.295
River Rch & RM=SYLVANRUN,Main      ,18995.6
1250.450
River Rch & RM=SYLVANRUN,Main      ,14130.3
1341.827
River Rch & RM=SYLVANRUN,Main      ,8329.5
1488.821
River Rch & RM=SYLVANRUN,Main      ,1187.1
1646.854
River Rch & RM=SYLVANRUN,Main      ,529.9
1649.828
Boundary for River Rch & Prof#=SYLVANRUN,Main      ,1
Up Type=0
Dn Type=3
Dn Slope=0.006919

--- SYLVANRUN.g01 (geometry) ---

Geom Title=USGS 10m DEM
Program Version=5.03

River Reach=SYLVANRUN       ,Main
Reach XY= 30
     2362444.667      298723.194     2362595.709      298922.847
     2363397.792      298954.097     2364486.334      298695.416
     2365449.876      299157.222     2366106.126      299007.916
     2366788.417      299372.499     2368633.933       299553.38
     2369198.139      300490.555     2369965.964      300426.383
     2370330.084      301608.611     2370828.348       301421.11
     2371407.891      301723.779     2371731.125      301487.083
     2373378.319      301510.454     2375432.138      300979.204
     2376478.724      301463.883     2377112.694      301135.454
     2377963.389      301005.245     2378094.998      300654.156
     2379138.512      300684.678      2379645.68      300411.496
     2379901.106       300654.84     2379924.688      301233.761
     2381520.174       301787.58     2381520.174      301978.553
     2382273.646      302568.831     2382791.007      302438.622
     2382883.021       302747.65     2383407.327      303131.331

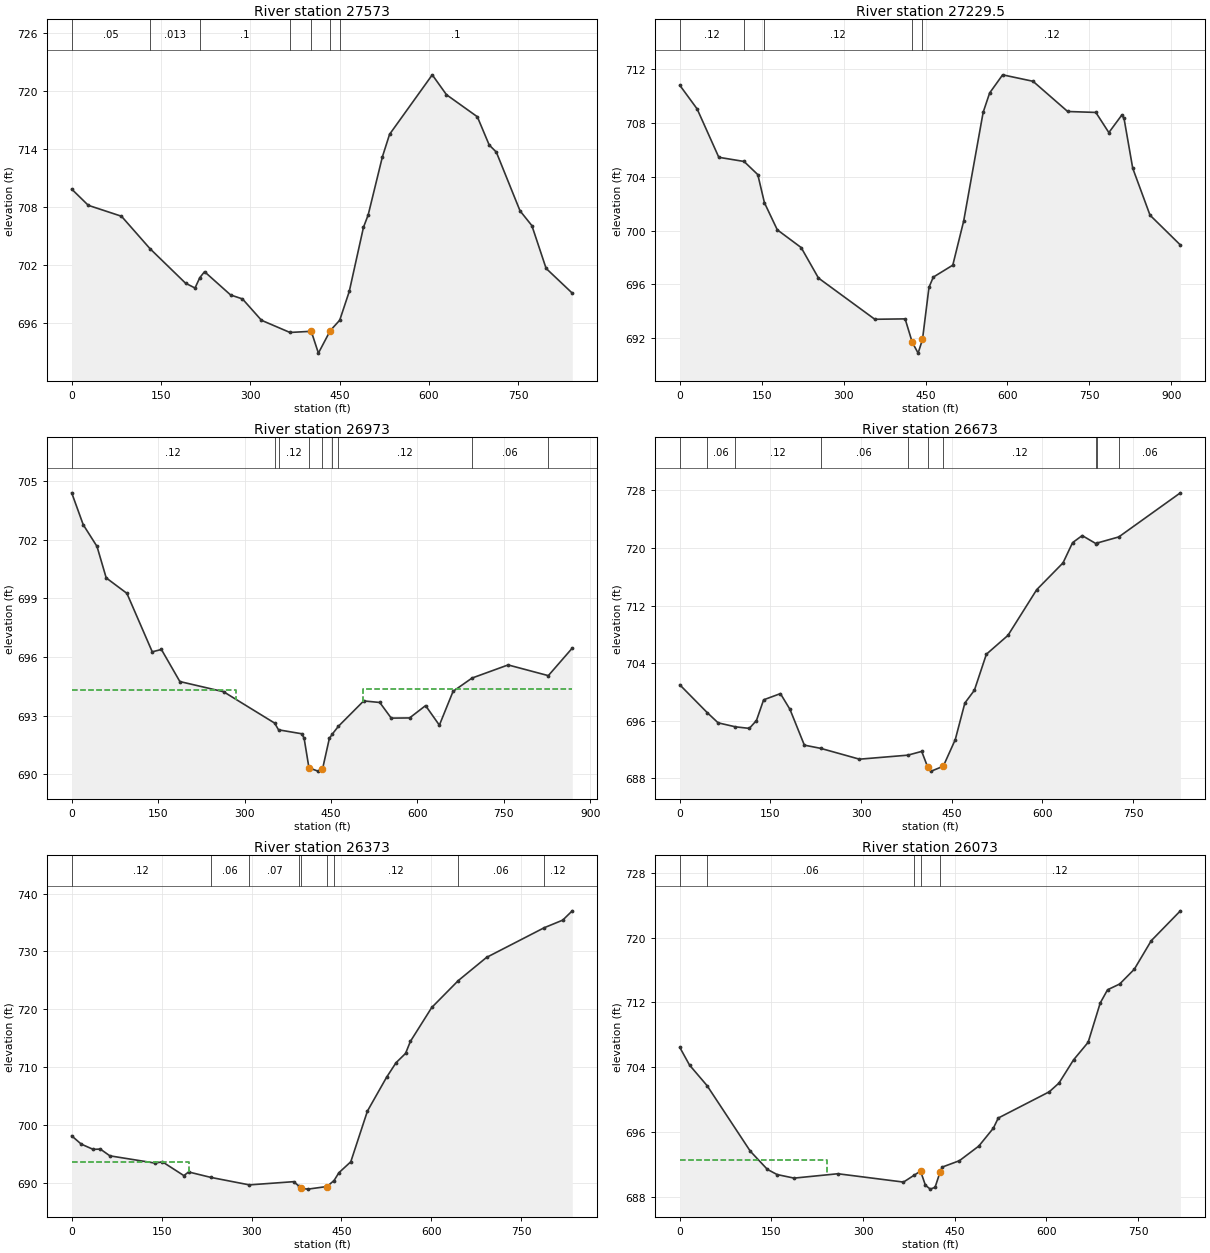
Type RM Length L Ch R = 1 ,27573   ,360.4,343.5,333
XS GIS Cut Line= 3
     2362072.517      298909.689     2362450.742      298731.137
     2362715.268      298401.957
#Sta/Elev= 30
       0  709.87    27.9  708.19    83.6  707.06   131.4  703.71   191.2  700.13
   207.1  699.63   215.1   700.7   223.1  701.32   266.9  698.91   286.8   698.5
   318.7  696.29   366.5  695.03   402.3  695.15   414.3  692.89   434.2  695.22
   450.1   696.3   466.1  699.27     490  705.92   497.9   707.2   521.8  713.22
   533.8  715.54   605.5   721.7   629.4  719.64   681.2  717.36   701.1  714.44
   713.1   713.7   752.9  707.62   772.8  706.09   796.7  701.66   840.6   699.1
#Mann= 7 ,-1 , 0
       0     .05       0   131.4    .013       0   215.1      .1       0
   366.5     .06       0   402.3    .045       0   434.2     .06       0
   450.1      .1       0
Bank Sta=402.3,434.2
XS Rating Curve= 0 ,0
Exp/Cntr=0.3,0.1

Type RM Length L Ch R = 1 ,27229.5 ,266.5,256.5,255.8
XS GIS Cut Line= 3
     2362566.002      299314.953      2362669.48       298838.04
     2362722.649      298412.693
#Sta/Elev= 30
       0  710.82    31.7  709.06    71.4  705.46  117.61705.1499   142.8  704.17
  154.93702.0793   178.5  700.06   222.2  698.74   253.9  696.47   357.1   693.4
   412.6  693.43   425.6  691.69   436.4  690.88   444.4   691.9   456.3  695.78
   464.2  696.54   499.9  697.43   519.8  700.71   555.5  708.81   567.4  710.25
   591.2   711.6   646.8  711.12   710.3  708.87   761.9   708.8   785.7   707.3
   809.5  708.61   813.5  708.35   829.4  704.65   861.1  701.15   916.7  698.93
#Mann= 5 ,-1 , 0
       0     .12       0  117.61    .016       0  154.93     .12       0
   425.6    .045       0   444.4     .12       0
Bank Sta=425.6,444.4
XS Rating Curve= 0 ,0
Exp/Cntr=0.3,0.1

Type RM Length L Ch R = 1 ,26973   ,290.1,300,302.2
XS GIS Cut Line= 3
     2362983.836      299299.835     2362873.063      298895.493
     2362841.264      298447.225
#Sta/Elev= 30
       0   704.4      20  702.77    43.9  701.66    59.9  700.05    95.8  699.26
   139.8  696.27   155.7  696.39   187.7  694.75   263.5  694.23  352.12692.6266
  358.92692.2824   399.3  692.08   403.3  691.85   411.7  690.34   427.2  690.17
   435.2  690.27   447.1  691.84  452.46692.0728  462.82692.4628   506.7  693.76
   534.6  693.68   554.5  692.88   586.3  692.89   614.1  693.52     638  692.52
   661.8  694.25  694.74694.9299   757.3   695.6  827.07695.0526   868.6  696.46
#Mann= 9 ,-1 , 0
       0     .12       0  352.12     .06       0  358.92     .12       0
   411.7    .045       0   435.2     .12       0  452.46     .06       0
  462.82     .12       0  694.74     .06       0  827.07     .12       0
#XS Ineff= 2 , 0
          285.86   694.3  504.64          694.38
Permanent Ineff=
       F       F
Bank Sta=411.7,435.2
XS Rating Curve= 0 ,0
Exp/Cntr=0.3,0.1

Type RM Length L Ch R = 1 ,26673   ,307,300,294.2
XS GIS Cut Line= 3
     2363063.333      299304.455     2363135.085      298890.482
      2363243.41      298496.885
#Sta/Elev= 30
       0  700.99   45.16697.1457    63.4  695.71    92.1695.1546     115  694.94
   126.8  696.03   138.7  698.91   166.5  699.77   182.3  697.58   206.1  692.61
  233.07692.1656   297.3  690.66  377.31691.2182   400.3  691.74  410.12689.5784
   416.2     689     436  689.68   455.8  693.37   471.7  698.46   487.5  700.24
   507.3  705.24     543  707.86   590.6  714.21   634.2  717.94     650  720.75
   665.9  721.73  688.54720.6197  690.28720.6876  726.45721.5416   828.4  727.67
#Mann= 10 ,-1 , 0
       0     .12       0   45.16     .06       0    92.1     .12       0
  233.07     .06       0  377.31     .12       0  410.12    .045       0
     436     .12       0  688.54     .06       0  690.28     .12       0
  726.45     .06       0
Bank Sta=410.12,436
XS Rating Curve= 0 ,0
Exp/Cntr=0.3,0.1

Type RM Length L Ch R = 1 ,26373   ,299.6,300,296
XS GIS Cut Line= 3
     2363476.175      299353.069     2363418.752      298951.102
     2363423.106      298522.061
#Sta/Elev= 30
       0  698.09    15.9  696.66    35.8  695.75    47.8   695.8    63.7  694.63
   139.3  693.37   151.3   693.6   187.1  691.21   195.1  691.84  231.88690.9051
  296.37689.6035   370.2  690.16  379.75689.3446   382.2  689.02   394.1  688.87
   425.9  689.32   437.7690.3559   445.8  691.71   465.6   693.6   493.4  702.38
   525.2   708.2   541.1  710.74     557  712.35     565  714.42   600.7   720.3
  645.06724.9609   692.1  728.96  788.32 734.096   819.2  735.41   835.1  737.02
#Mann= 9 ,-1 , 0
       0     .12       0  231.88     .06       0  296.37     .07       0
  379.75     .04       0   382.2    .045       0   425.9     .04       0
   437.7     .12       0  645.06     .06       0  788.32     .12       0
#XS Ineff= 2 , 0
          195.05  693.48
Permanent Ineff=
       F       F
Bank Sta=382.2,425.9
XS Rating Curve= 0 ,0
Exp/Cntr=0.3,0.1

Type RM Length L Ch R = 1 ,26073   ,300.6,300,300.4
XS GIS Cut Line= 3
     2363761.301      299289.922     2363709.922      298883.267
     2363642.611      298479.406
#Sta/Elev= 30
       0  706.44    15.9  704.26   44.64701.7176   115.4  693.62   143.3  691.38
   159.2  690.74     187   690.3   258.7  690.84   366.1  689.81  383.27690.6458
     394  691.17   401.9  689.43   409.9  688.94   417.8  689.17   425.8  691.01
   429.8  691.67   457.6  692.45   489.4  694.26   513.2  696.47   521.2  697.72
   604.7  700.96   620.6  702.04   644.4   704.9   668.3  707.07   688.1  711.93
   700.1  713.56   719.9  714.27   743.8  716.09   771.6  719.62   819.3  723.31
#Mann= 5 ,-1 , 0
       0    .016       0   44.64     .06       0  383.27     .12       0
     394    .045       0   425.8     .12       0
#XS Ineff= 2 , 0
          240.45   692.5
Permanent Ineff=
       F       F
Bank Sta=394,425.8
XS Rating Curve= 0 ,0
Exp/Cntr=0.3,0.1

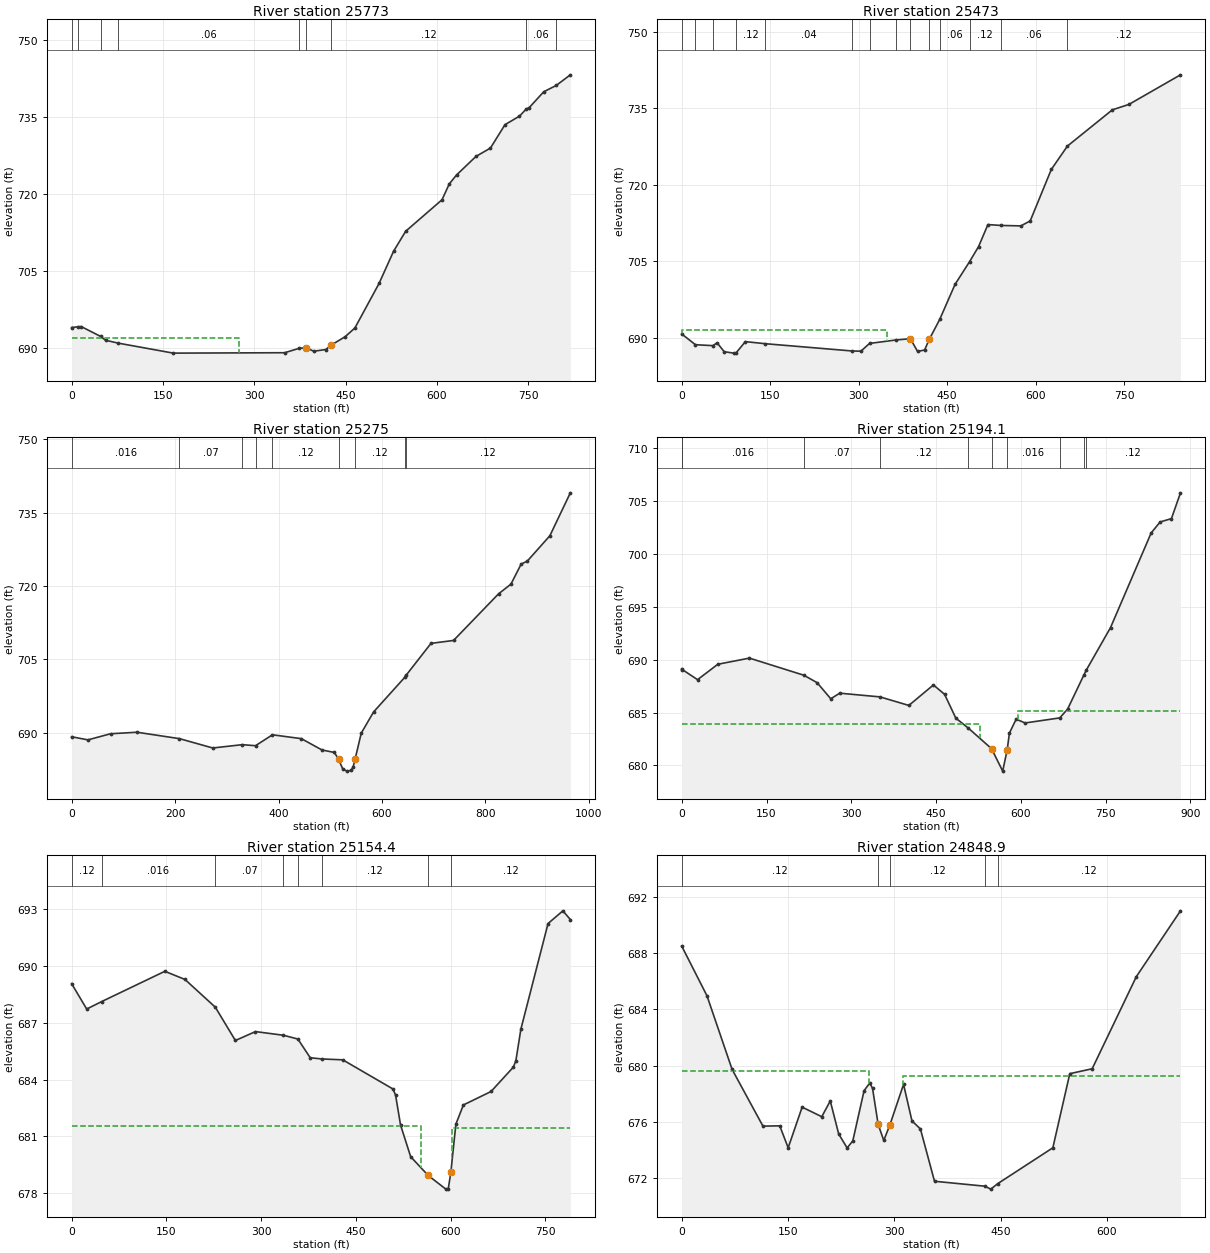
Type RM Length L Ch R = 1 ,25773   ,297.4,300,292.6
XS GIS Cut Line= 3
     2364045.513      299254.517     2363998.573      298847.716
     2363951.633      298440.916
#Sta/Elev= 30
       0   693.9   10.36694.0565    15.9  694.09   47.89 692.161    55.7  691.43
    76.6690.8663     167  688.92   349.9     689  374.14689.8743   385.6  689.95
   397.6  689.29   417.4  689.62   425.4  690.42   449.3  692.13   465.2  693.82
   504.9   702.5   528.8  708.79   548.6  712.67   608.3  718.81   620.2   721.9
   632.1  723.63     664  727.25   687.8  728.88   711.7  733.44   735.5   735.1
  746.57736.4875   751.4  736.75   775.3  739.85  795.75741.0722     819  743.15
#Mann= 9 ,-1 , 0
       0     .12       0   10.36    .016       0   47.89     .12       0
    76.6     .06       0  374.14     .12       0   385.6    .045       0
   425.4     .12       0  746.57     .06       0  795.75     .12       0
#XS Ineff= 2 , 0
          275.54  691.82
Permanent Ineff=
       F       F
Bank Sta=385.6,425.4
XS Rating Curve= 0 ,0
Exp/Cntr=0.3,0.1

Type RM Length L Ch R = 1 ,25473   ,175.1,198,209.2
XS GIS Cut Line= 3
     2364297.195      299225.936     2364297.195      298822.152
     2364118.639       298417.94
#Sta/Elev= 30
       0   690.7   23.24688.5913   52.76688.4103      60  688.96      72  687.22
      88  686.94    92.2 686.996   107.9   689.2  141.31 688.793  288.91687.3633
   303.8  687.32  318.43688.8437  363.29689.5211   387.8  689.77   399.8  687.28
   411.8  687.55   419.7  689.64  437.42693.5522   463.5  700.45  488.02704.8901
   503.3  707.85   519.2  712.18  541.67712.0071     575  711.92   590.9   712.9
   626.7  723.01  654.01727.5933   730.2  734.71   758.1  735.76   845.7  741.58
#Mann= 14 ,-1 , 0
       0    .016       0   23.24     .12       0   52.76     .04       0
    92.2     .12       0  141.31     .04       0  288.91     .12       0
  318.43     .06       0  363.29     .12       0   387.8    .045       0
   419.7     .12       0  437.42     .06       0  488.02     .12       0
  541.67     .06       0  654.01     .12       0
#XS Ineff= 2 , 0
          348.81  691.47
Permanent Ineff=
       F       F
Bank Sta=387.8,419.7
XS Rating Curve= 0 ,0
Exp/Cntr=0.3,0.1

Type RM Length L Ch R = 1 ,25275   ,101.9,80.9,81.3
XS GIS Cut Line= 4
      2364338.21      299224.688     2364418.129      298934.919
     2364429.072      298647.832     2364140.009      298406.946
#Sta/Elev= 30
       0  689.17    31.6  688.53    75.2  689.78   126.6  690.09  208.49688.7814
   272.9  686.87  330.04687.5485  355.53687.3376  388.25689.5689   444.2  688.78
   484.1  686.46   508.1  685.96   516.1  684.56     524  682.63     532  682.14
     540  682.29     544   682.9     548  684.55     560  689.92   583.9  694.25
  643.98701.3022  646.45701.7097   694.8  708.26   738.4  708.86   825.5   718.4
   849.3  720.36   869.1  724.47     881  725.08   924.6  730.26   964.2  739.04
#Mann= 9 ,-1 , 0
       0    .016       0  208.49     .07       0  330.04     .12       0
  355.53     .07       0  388.25     .12       0   516.1    .045       0
     548     .12       0  643.98     .06       0  646.45     .12       0
Bank Sta=516.1,548
XS Rating Curve= 0 ,0
Exp/Cntr=0.3,0.1

Type RM Length L Ch R = 1 ,25194.1 ,43.8,39.6,39.7
XS GIS Cut Line= 5
     2364345.805      299224.688     2364425.016      298952.336
     2364497.037      298885.149     2364512.345      298600.802
      2364340.38      298470.565
#Sta/Elev= 30
       0  689.13    1.21689.0574      28  688.11    63.9  689.57   119.8  690.15
  216.12688.5295   239.7  687.82   263.7   686.3   279.6  686.83  350.83686.4788
   401.9  685.67   445.4  687.61   465.2  686.72     485  684.47  507.27683.5172
   548.2  681.58     568  679.45   575.9  681.46   579.9  683.05   591.8  684.37
   607.6  684.01  668.99684.4897   682.9  685.33  711.51688.5352  715.85689.0087
   758.8  693.04   830.7     702   846.6  703.04   866.6  703.36   882.6   705.8
#Mann= 10 ,-1 , 0
       0     .12       0    1.21    .016       0  216.12     .07       0
  350.83     .12       0  507.27    .016       0   548.2    .045       0
   575.9    .016       0  668.99     .12       0  711.51     .06       0
  715.85     .12       0
#XS Ineff= 2 , 0
          527.35  683.93  594.43          685.17
Permanent Ineff=
       F       F
Bank Sta=548.2,575.9
XS Rating Curve= 0 ,0
Exp/Cntr=0.3,0.1

Type RM Length L Ch R = 1 ,25154.4 ,300.5,305.6,305.8
XS GIS Cut Line= 5
     2364354.486      299227.944     2364435.866      298956.676
     2364535.714      298886.209     2364550.968       298616.03
     2364621.413      298526.989
#Sta/Elev= 30
       0  689.06    23.9  687.72   47.35 688.109   147.6  689.71   179.5  689.28
  227.53687.8161   259.3  686.06   291.1  686.53  335.43686.3361  358.26686.1372
   377.8  685.15   396.2685.0867   429.3  685.04   508.9   683.5   512.9  683.18
   520.8   681.6   536.8  679.93   564.6  678.94   592.5  678.22   596.4  678.25
   600.4   679.1   608.4  681.65   620.3  682.66   664.1  683.37   699.5  684.66
   703.4     685   711.3  686.66   754.3  692.23   777.8   692.9   789.6  692.44
#Mann= 8 ,-1 , 0
       0     .12       0   47.35    .016       0  227.53     .07       0
  335.43     .12       0  358.26    .016       0   396.2     .12       0
   564.6    .045       0   600.4     .12       0
#XS Ineff= 2 , 0
          553.15  681.54  602.68          681.43
Permanent Ineff=
       F       F
Bank Sta=564.6,600.4
XS Rating Curve= 0 ,0
Exp/Cntr=0.3,0.1

Type RM Length L Ch R = 1 ,24848.9 ,253.6,257.3,261.2
XS GIS Cut Line= 4
      2364734.26      299201.902     2364727.249      299016.321
     2364762.405      298632.207     2364653.965      298556.286
#Sta/Elev= 30
       0  688.49    35.6  684.96    71.1  679.72   114.6  675.69   138.3  675.71
   150.2  674.15   169.9  677.04   197.6  676.36   209.6  677.48   221.5  675.13
   233.4  674.14   241.4  674.64   257.3  678.21   265.2  678.75   269.2  678.39
   277.2  675.81   285.1  674.67  293.87675.7963     313  678.66   324.9  676.06
   336.8  675.49   356.7  671.77  427.66671.4188   436.2  671.21  445.81671.5963
   523.7  674.15   547.6  679.42   579.2  679.77   641.5  686.32   703.8     691
#Mann= 5 ,-1 , 0
       0     .12       0   277.2    .045       0  293.87     .12       0
  427.66     .06       0  445.81     .12       0
#XS Ineff= 2 , 0
          264.19  679.59  312.07          679.29
Permanent Ineff=
       F       F
Bank Sta=277.2,293.87
XS Rating Curve= 0 ,0
Exp/Cntr=0.3,0.1

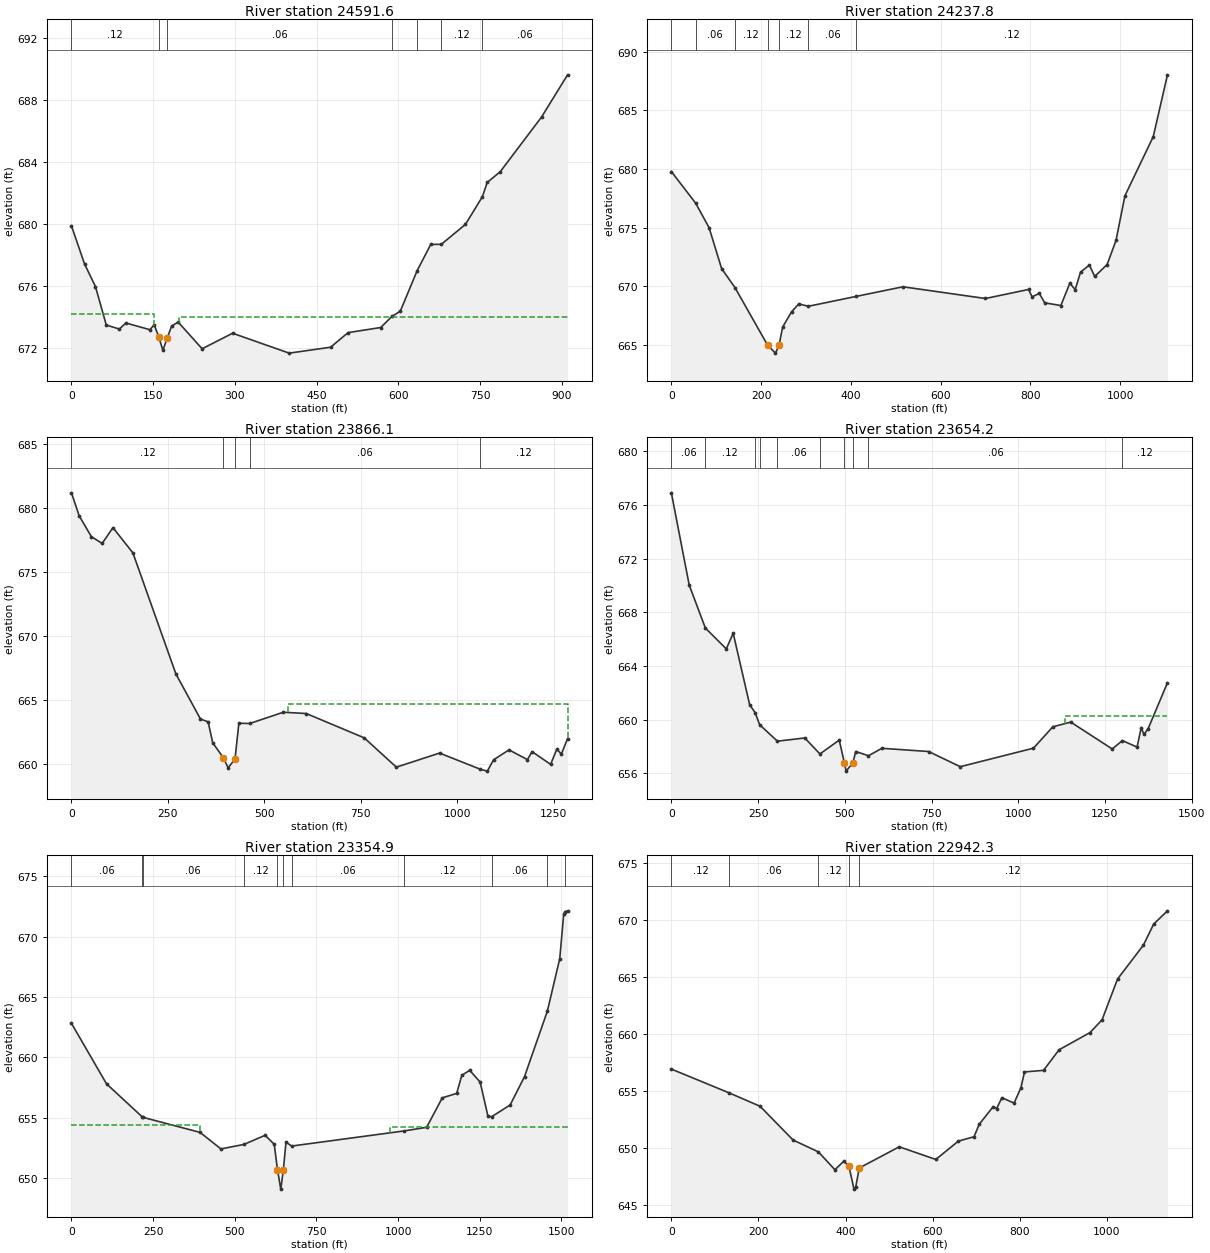
Type RM Length L Ch R = 1 ,24591.6 ,360.2,353.8,347.3
XS GIS Cut Line= 3
     2364931.676      299176.477     2365093.134      298561.894
     2364960.322      298321.009
#Sta/Elev= 30
       0  679.87      24  677.42      44  675.97    63.9  673.49    87.9  673.23
    99.9  673.62   143.9  673.19   151.9   673.5     160  672.74   167.8  671.86
   175.8  672.67   183.8  673.42   195.8  673.68   239.8  671.96   295.7  672.96
   399.6  671.68   475.6  672.06   507.6     673   567.5  673.33  588.06674.0396
   603.5  674.38  634.51676.9977   659.4  678.68  678.78678.6852   723.1  679.97
  754.14681.7505     763  682.67   786.9  683.36   862.7  686.88   910.5   689.6
#Mann= 7 ,-1 , 0
       0     .12       0     160    .045       0   175.8     .06       0
  588.06     .12       0  634.51     .06       0  678.78     .12       0
  754.14     .06       0
#XS Ineff= 2 , 0
          150.67  674.22  198.14          673.99
Permanent Ineff=
       F       F
Bank Sta=160,175.8
XS Rating Curve= 0 ,0
Exp/Cntr=0.3,0.1

Type RM Length L Ch R = 1 ,24237.8 ,361.5,371.7,381.6
XS GIS Cut Line= 3
     2365310.582      299327.519      2365315.79      298427.779
     2365186.884      298267.623
#Sta/Elev= 30
       0  679.79   54.07677.0944      84  675.01     112  671.51  141.77669.8882
   214.7  664.96   231.9   664.3   239.9  664.96   247.9  666.52   267.9  667.83
   283.9   668.5  305.27668.2972  411.98 669.141   515.9  669.96   699.8  668.96
   795.8  669.73   803.8   669.1   819.8   669.4   831.8  668.59   867.8  668.36
   887.8  670.26   899.8  669.72   911.6   671.2   931.4  671.82   943.2  670.84
   970.9  671.86   990.7  673.91  1010.5  677.72  1073.7  682.77  1105.3  688.04
#Mann= 7 ,-1 , 0
       0     .12       0   54.07     .06       0  141.77     .12       0
   214.7    .045       0   239.9     .12       0  305.27     .06       0
  411.98     .12       0
Bank Sta=214.7,239.9
XS Rating Curve= 0 ,0
Exp/Cntr=0.3,0.1

Type RM Length L Ch R = 1 ,23866.1 ,217.9,211.9,204.2
XS GIS Cut Line= 4
     2365455.113      299423.873     2365643.915      298942.102
     2365645.405      298637.416     2365374.384      298261.113
#Sta/Elev= 30
       0  681.16    19.9  679.37    51.7  677.73    79.6  677.21   107.5  678.44
   159.2  676.47   270.7  667.01   334.4  663.49   354.2  663.27   366.2  661.63
     394  660.45     406  659.68   423.9  660.36   433.9  663.16  462.13663.1407
   549.1  664.02   608.5  663.92   758.8  662.02   842.1  659.73   954.1  660.83
 1060.03 659.564    1078  659.42    1094   660.3    1134  661.08  1181.9  660.32
  1193.9  660.94  1241.9  659.95  1257.9  661.12  1269.9  660.76  1285.9  661.96
#Mann= 5 ,-1 , 0
       0     .12       0     394    .045       0   423.9     .12       0
  462.13     .06       0 1060.03     .12       0
#XS Ineff= 2 , 0
                          560.58          664.63
Permanent Ineff=
       F       F
Bank Sta=394,423.9
XS Rating Curve= 0 ,0
Exp/Cntr=0.3,0.1

Type RM Length L Ch R = 1 ,23654.2 ,298.7,299.3,298.7
XS GIS Cut Line= 5
     2365629.593      299524.134     2365785.831      299319.579
     2365810.798      299062.439     2365821.046      298749.396
      2365472.04      298259.811
#Sta/Elev= 30
       0  676.89    51.5  670.02   98.02666.8237   158.4  665.27   178.2  666.44
   225.7  661.12  241.56660.5212  254.53659.6237  305.82 658.399   384.6  658.64
  428.29657.4499     484  658.48  498.75656.7892   503.8  656.17   523.2  656.79
   531.6  657.63  568.24657.3152   606.9  657.87   741.7  657.63   832.9   656.5
    1044  657.88  1099.7  659.47  1151.5  659.82  1270.9  657.82 1300.25658.4436
  1342.6  657.96  1354.6  659.41  1362.5   658.9  1374.5  659.33  1430.2  662.75
#Mann= 10 ,-1 , 0
       0     .06       0   98.02     .12       0  241.56     .06       0
  254.53     .12       0  305.82     .06       0  428.29     .12       0
  498.75    .045       0   523.2     .12       0  568.24     .06       0
 1300.25     .12       0
#XS Ineff= 2 , 0
                         1136.02          660.24
Permanent Ineff=
       F       F
Bank Sta=498.75,523.2
XS Rating Curve= 0 ,0
Exp/Cntr=0.3,0.1

Type RM Length L Ch R = 1 ,23354.9 ,401.7,412.6,421.7
XS GIS Cut Line= 4
     2365890.009      299578.821     2366061.741      299413.447
     2366112.665      298666.061     2366564.488      298386.113
#Sta/Elev= 30
       0  662.82   107.3  657.81  216.68655.0728  217.75655.0434   393.8  653.79
   457.6  652.42  527.74652.7907     593  653.55   620.9   652.8   630.8   650.7
   640.9  649.09   648.8  650.69   656.8  652.98  674.24652.6584 1018.99653.9111
  1087.4  654.21  1135.4  656.65  1179.4  657.02  1195.3  658.52  1219.3  658.93
  1251.3  657.96  1275.3  655.12 1287.38   655.1  1343.2  656.06  1387.2  658.41
 1456.99663.8215  1495.1  668.18  1507.1  671.84 1512.67672.0814    1519  672.14
#Mann= 11 ,-1 , 0
       0     .06       0  216.68     .12       0  217.75     .06       0
  527.74     .12       0   630.8    .045       0   648.8     .12       0
  674.24     .06       0 1018.99     .12       0 1287.38     .06       0
 1456.99     .12       0 1512.67     .06       0
#XS Ineff= 2 , 0
          394.63  654.38  975.85          654.22
Permanent Ineff=
       F       F
Bank Sta=630.8,648.8
XS Rating Curve= 0 ,0
Exp/Cntr=0.3,0.1

Type RM Length L Ch R = 1 ,22942.3 ,449.2,440.8,432.1
XS GIS Cut Line= 3
     2366237.665      299554.082     2366624.826       298814.73
     2366668.655      298513.717
#Sta/Elev= 30
       0   656.9  133.31654.8043   203.7  653.64   279.5  650.68   337.6649.6425
   375.4  648.08   395.3  648.81   407.3  648.43   419.3  646.38   423.3  646.58
   431.3  648.23   523.1  650.09     607  648.98   658.9  650.59   694.8  650.97
   706.8  652.07   738.8  653.61   746.7  653.44   758.7  654.39   786.7  653.92
   802.6  655.28   810.6  656.65   854.3  656.79   889.9  658.59     961   660.1
   988.7  661.22  1024.2  664.79  1083.5  667.76  1107.2  669.61  1138.8  670.77
#Mann= 5 ,-1 , 0
       0     .12       0  133.31     .06       0   337.6     .12       0
   407.3    .045       0   431.3     .12       0
Bank Sta=407.3,431.3
XS Rating Curve= 0 ,0
Exp/Cntr=0.3,0.1

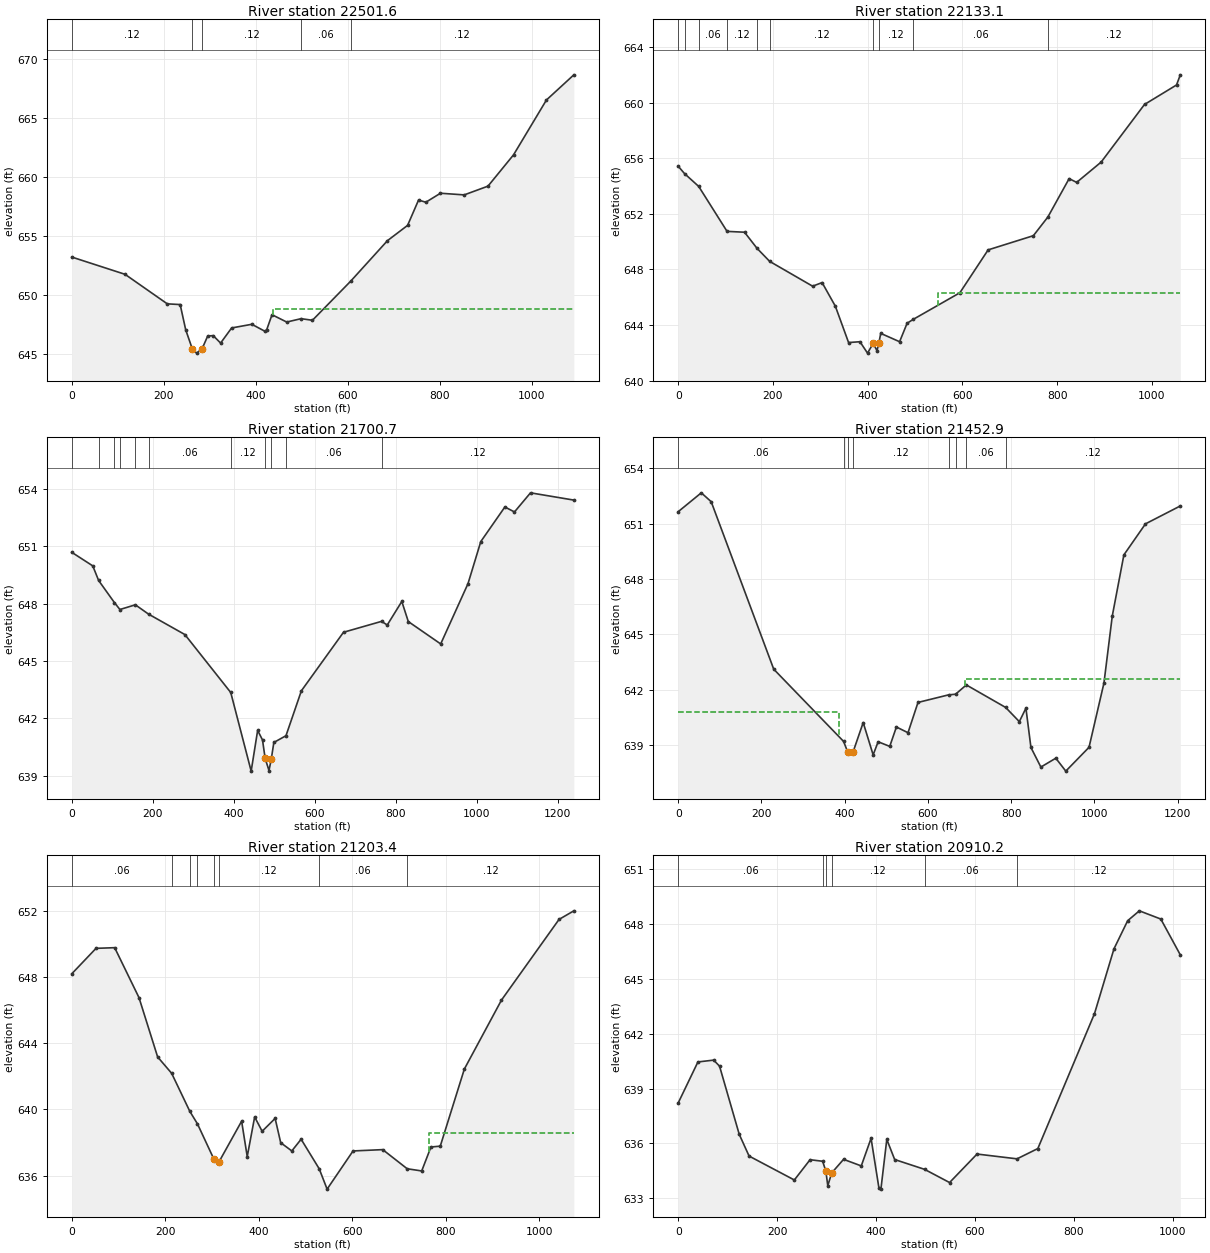
Type RM Length L Ch R = 1 ,22501.6 ,363.3,368.5,368.9
XS GIS Cut Line= 3
     2366788.447      299645.227      2366840.53      299072.311
      2366746.78      298564.498
#Sta/Elev= 30
       0  653.21   115.8  651.75   207.7  649.25   235.7  649.19   247.7  647.06
   262.4   645.4   271.7  645.08   283.6  645.47   295.6  646.53   307.6  646.56
   323.6  645.93   347.6  647.21   391.5  647.52   419.5  646.94   423.5  647.02
   435.4  648.33   467.4  647.71  498.62647.9958   523.3  647.86  606.38651.1638
   686.5   654.6   730.2  655.89     754  658.03   769.9  657.85   801.7  658.61
   853.3  658.47     905  659.21   960.6  661.86  1032.1   666.5  1091.7  668.63
#Mann= 5 ,-1 , 0
       0     .12       0   262.4    .045       0   283.6     .12       0
  498.62     .06       0  606.38     .12       0
#XS Ineff= 2 , 0
                          437.15           648.8
Permanent Ineff=
       F       F
Bank Sta=262.4,283.6
XS Rating Curve= 0 ,0
Exp/Cntr=0.3,0.1

Type RM Length L Ch R = 1 ,22133.1 ,422.8,432.4,430.5
XS GIS Cut Line= 3
     2367076.051      299760.344     2367137.872      299349.367
     2367130.895      298705.123
#Sta/Elev= 30
       0  655.42    13.3654.8918   43.22653.9698  103.07650.7391   139.9  650.68
  166.36649.5215  193.02648.5839   283.7   646.8   303.7  647.06   331.7  645.36
   359.6  642.75   383.6  642.81   399.6  641.99   411.6  642.69   419.6  642.16
   423.6  642.73   427.5  643.41   467.3  642.81   483.2  644.14  496.58644.4255
   594.6  646.33   654.2  649.41   749.7  650.43  780.31651.7705   825.2  654.53
   841.1  654.26   892.8  655.72   984.3  659.86  1051.9  661.26  1059.9  661.99
#Mann= 10 ,-1 , 0
       0     .06       0    13.3     .08       0   43.22     .06       0
  103.07     .12       0  166.36     .06       0  193.02     .12       0
   411.6    .045       0   423.6     .12       0  496.58     .06       0
  780.31     .12       0
#XS Ineff= 2 , 0
                          547.37          646.33
Permanent Ineff=
       F       F
Bank Sta=411.6,423.6
XS Rating Curve= 0 ,0
Exp/Cntr=0.3,0.1

Type RM Length L Ch R = 1 ,21700.7 ,250,247.8,245.5
XS GIS Cut Line= 4
     2367231.155      299748.092      2367459.02      299460.332
     2367675.165      298952.519     2367431.535      298743.803
#Sta/Elev= 30
       0  650.68    51.9  649.97    66.3649.2075  105.34648.0503  118.88  647.69
  157.03 647.935  189.56647.4488   279.3  646.38  392.57643.3508     443  639.24
     459  641.37     471  640.87   477.5  639.91     487  639.27   492.5  639.85
     499  640.74  528.93641.0896     567  643.44     671   646.5  764.99647.0698
     779  646.88     815  648.11     831  647.06     911  645.89   978.4  649.04
    1010  651.24  1069.5  653.05  1093.2  652.79  1132.8  653.79  1239.8  653.41
#Mann= 11 ,-1 , 0
       0     .12       0    66.3     .06       0  105.34     .08       0
  118.88     .12       0  157.03     .08       0  189.56     .06       0
  392.57     .12       0   477.5    .045       0   492.5     .12       0
  528.93     .06       0  764.99     .12       0
Bank Sta=477.5,492.5
XS Rating Curve= 0 ,0
Exp/Cntr=0.3,0.1

Type RM Length L Ch R = 1 ,21452.9 ,250.1,249.5,249
XS GIS Cut Line= 4
      2367709.02      299905.644     2367660.843      299608.769
     2367816.951      299122.275      2368053.93      298806.303
#Sta/Elev= 30
       0  651.65    55.4  652.67    79.2  652.19   229.5  643.12  397.26639.2119
   407.4  638.63   420.5  638.66   444.5  640.23   468.4  638.48   480.4  639.19
   508.3  638.94   524.3  639.99   552.2  639.68   576.2  641.32  649.51641.7289
  666.53641.7653  692.35642.2678   786.9 641.048   819.7  640.28   835.6  641.01
   847.6  638.88   871.5  637.82   907.4   638.3   931.4   637.6   987.2  638.89
  1023.1  642.37  1043.1     646    1071  649.31  1122.9  650.99  1206.6  651.96
#Mann= 8 ,-1 , 0
       0     .06       0  397.26     .12       0   407.4    .045       0
   420.5     .12       0  649.51     .06       0  666.53     .12       0
  692.35     .06       0   786.9     .12       0
#XS Ineff= 2 , 0
          385.76   640.8  689.16          642.57
Permanent Ineff=
       F       F
Bank Sta=407.4,420.5
XS Rating Curve= 0 ,0
Exp/Cntr=0.3,0.1

Type RM Length L Ch R = 1 ,21203.4 ,299.5,293.2,286.5
XS GIS Cut Line= 4
      2367837.23      299882.207     2367951.216      299482.867
     2368060.994      299118.008      2368053.93      298840.157
#Sta/Elev= 30
       0  648.21    51.9  649.75    91.8  649.79   143.8  646.77   183.7  643.18
  213.72 642.187  252.58639.8859  268.94 639.128   303.5  637.03   315.4  636.85
   363.4  639.29   375.4  637.15   391.3  639.55   407.3  638.68   435.1  639.46
     447  637.99   470.8  637.49   490.7   638.2  529.35 636.413   546.3  635.18
   601.8  637.49   665.3  637.57   717.7 636.412   748.7  636.28   768.5  637.73
   788.4  637.78     840  642.45   919.4  646.62  1042.5   651.5  1074.2  652.02
#Mann= 8 ,-1 , 0
       0     .06       0  213.72     .12       0  252.58     .06       0
  268.94     .12       0   303.5    .045       0   315.4     .12       0
  529.35     .06       0   717.7     .12       0
#XS Ineff= 2 , 0
                          764.09          638.59
Permanent Ineff=
       F       F
Bank Sta=303.5,315.4
XS Rating Curve= 0 ,0
Exp/Cntr=0.3,0.1

Type RM Length L Ch R = 1 ,20910.2 ,263.5,264.2,273.6
XS GIS Cut Line= 4
     2368206.979      299916.713     2368208.167      299506.972
     2368201.417      299162.125     2368257.055      298907.865
#Sta/Elev= 30
       0  638.22    39.8  640.46    71.6  640.56    83.5  640.23   123.3   636.5
   143.2  635.31   234.7     634   266.5  635.11  291.94635.0247   298.4  634.48
   302.3  633.69   310.3634.3878   334.2  635.13     370  634.77   389.8  636.28
   405.8  633.54   409.7   633.5   421.6  636.22   437.5  635.12     498 634.582
   548.5  633.86     604  635.42  684.87635.1572   726.9  635.72   841.4   643.1
   880.8  646.65   908.5  648.19   932.1  648.73   975.5  648.28  1014.9  646.32
#Mann= 6 ,-1 , 0
       0     .06       0  291.94     .12       0   298.4    .045       0
   310.3     .12       0     498     .06       0  684.87     .12       0
Bank Sta=298.4,310.3
XS Rating Curve= 0 ,0
Exp/Cntr=0.3,0.1

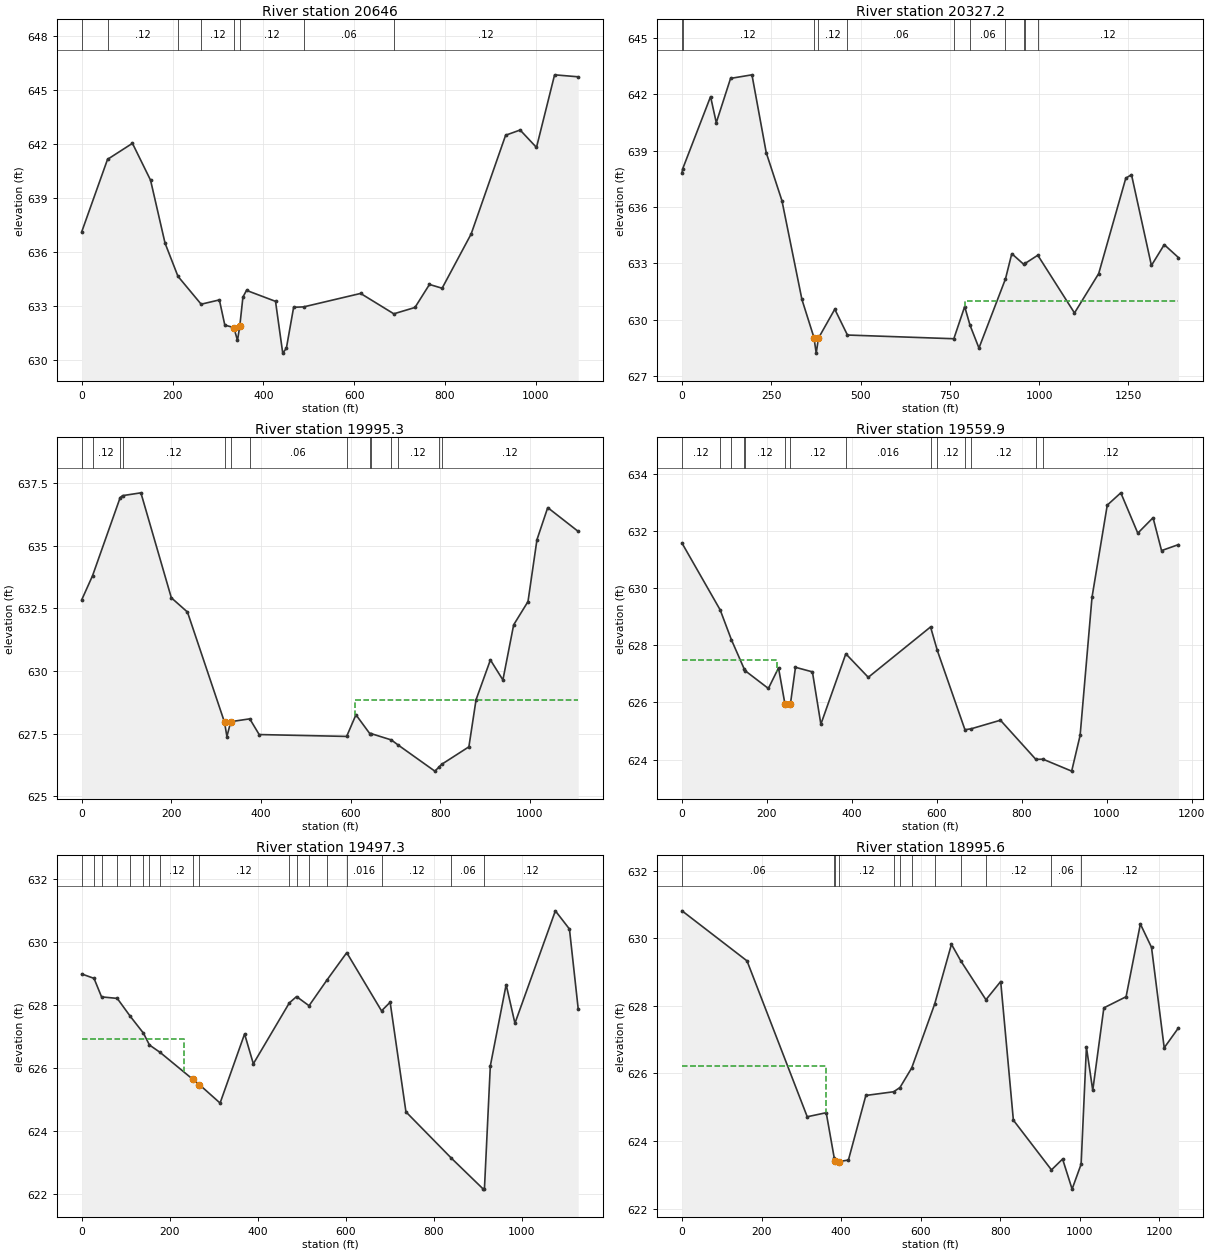
Type RM Length L Ch R = 1 ,20646   ,304.5,318.8,321.9
XS GIS Cut Line= 3
     2368461.624      299955.123     2368475.805      299161.338
     2368280.493      298933.907
#Sta/Elev= 30
       0  637.12   56.82641.1492   111.7  642.04   151.6  639.99   183.5  636.49
  211.99 634.642  263.06633.0912   303.2  633.33   315.2  631.93   335.1  631.79
   343.1  631.08   348.1631.8566   355.1  633.49     363  633.86   426.9  633.25
   442.8  630.37   450.8  630.64   466.8  632.92  488.83632.9419   614.4  633.69
  687.52632.5569   734.1  632.91     766  634.19   793.9  633.98   857.9     637
   933.8  642.49   965.8  642.78  1001.8  641.81  1041.7  645.85  1093.7  645.74
#Mann= 8 ,-1 , 0
       0     .06       0   56.82     .12       0  211.99     .06       0
  263.06     .12       0   335.1    .045       0   348.1     .12       0
  488.83     .06       0  687.52     .12       0
Bank Sta=335.1,348.1
XS Rating Curve= 0 ,0
Exp/Cntr=0.3,0.1

Type RM Length L Ch R = 1 ,20327.2 ,322.2,331.9,341.5
XS GIS Cut Line= 3
     2368499.384      299952.519     2369046.118      299135.296
     2369452.368      299157.865
#Sta/Elev= 30
       0  637.83    1.91638.0353    79.9  641.88    95.9  640.49   135.9  642.85
   195.8  643.04   235.8  638.89   279.8  636.33   335.7  631.07   369.4  629.04
   375.7  628.21  382.03629.0103   427.7  630.55  463.15629.1744  761.06628.9766
   791.4  630.69  806.36629.6992   831.4  628.48  905.68632.1683   923.3  633.51
  956.76632.9419  960.66632.9902   996.1633.4265  1098.9  630.35  1166.7  632.45
  1242.5  637.53  1258.5  637.72  1314.3  632.88  1350.2  633.99  1390.1   633.3
#Mann= 11 ,-1 , 0
       0     .06       0    1.91     .12       0   369.4    .045       0
  382.03     .12       0  463.15     .06       0  761.06    .016       0
  806.36     .06       0  905.68     .08       0  956.76     .12       0
  960.66     .06       0   996.1     .12       0
#XS Ineff= 2 , 0
                          791.74          630.97
Permanent Ineff=
       F       F
Bank Sta=369.4,382.03
XS Rating Curve= 0 ,0
Exp/Cntr=0.3,0.1

Type RM Length L Ch R = 1 ,19995.3 ,394.8,435.5,410.9
XS GIS Cut Line= 2
     2368649.124      300067.102      2369572.16       299454.74
#Sta/Elev= 30
       0  632.84   24.11633.8014   85.73636.9203   90.98636.9973     132  637.11
   199.9  632.92   235.9  632.35   318.6  627.95   323.9  627.38  332.47627.9739
  374.91628.0872   395.9  627.46  591.07627.3854   611.8  628.25  643.02627.4897
  644.89627.5018  690.81627.2449  705.57627.0479   787.8     626   796.6 626.152
  802.91  626.27   863.8  626.97   879.8  628.85   911.8  630.44   939.7  629.64
   963.7  631.84   995.7  632.77  1015.7  635.24  1039.7  636.52  1107.7  635.57
#Mann= 14 ,-1 , 0
       0     .06       0   24.11     .12       0   85.73     .06       0
   90.98     .12       0   318.6    .045       0  332.47     .12       0
  374.91     .06       0  591.07    .016       0  643.02     .06       0
  644.89     .12       0  690.81     .06       0  705.57     .12       0
   796.6     .06       0  802.91     .12       0
#XS Ineff= 2 , 0
                          610.53          628.82
Permanent Ineff=
       F       F
Bank Sta=318.6,332.47
XS Rating Curve= 0 ,0
Exp/Cntr=0.3,0.1

Type RM Length L Ch R = 1 ,19559.9 ,90.1,62.6,122.8
XS GIS Cut Line= 3
      2368784.54      300237.675     2369333.965      300165.678
     2369587.785      299605.782
#Sta/Elev= 30
       0  631.57   89.86629.2352  116.22628.1952  145.92627.1874  148.08627.1168
   203.3  626.49   227.2  627.21  242.48625.9337   255.1  625.94   267.1  627.23
     307  627.07   326.9  625.24  385.65627.7021   438.5  626.88  585.14628.6408
  601.07627.8184  666.12625.0478  680.38625.0788   749.7  625.38  833.05624.0104
  849.93624.0172   917.4   623.6   937.3  624.85   965.3  629.68  1001.2   632.9
  1033.1  633.33  1073.1  631.92    1109  632.46    1129  631.31  1168.9  631.52
#Mann= 14 ,-1 , 0
       0     .12       0   89.86     .06       0  116.22     .12       0
  145.92     .06       0  148.08     .12       0  242.48    .045       0
   255.1     .12       0  385.65    .016       0  585.14     .08       0
  601.07     .12       0  666.12    .016       0  680.38     .12       0
  833.05     .06       0  849.93     .12       0
#XS Ineff= 2 , 0
          222.91  627.49
Permanent Ineff=
       F       F
Bank Sta=242.48,255.1
XS Rating Curve= 0 ,0
Exp/Cntr=0.3,0.1

Type RM Length L Ch R = 1 ,19497.3 ,534.3,501.7,379.1
XS GIS Cut Line= 3
     2368791.572       300300.87     2369354.072       300213.63
     2369614.347      299718.456
#Sta/Elev= 30
       0  628.99   27.93628.8498   45.05  628.26   80.72628.2124  110.52627.6379
  140.31627.1046  153.99626.7276  178.27626.4921   252.2  625.64   267.2  625.47
   314.5  624.88   370.2  627.08   390.1  626.13  471.86628.0678  488.29628.2702
  516.75627.9788  557.45 628.797  602.45629.6681  681.51627.8154   701.1  628.09
     737   624.6  840.49623.1226   912.9  622.14  915.46622.1464   928.8  626.06
   964.8  628.65   984.8  627.42  1076.7     631  1108.7  630.42  1128.6  627.88
#Mann= 18 ,-1 , 0
       0     .06       0   27.93     .12       0   45.05     .06       0
   80.72     .08       0  110.52    .016       0  140.31     .06       0
  153.99    .016       0  178.27     .12       0   252.2    .045       0
   267.2     .12       0  471.86    .016       0  488.29     .12       0
  516.75     .06       0  557.45     .12       0  602.45    .016       0
  681.51     .12       0  840.49     .06       0  915.46     .12       0
#XS Ineff= 2 , 0
          231.58  626.92
Permanent Ineff=
       F       F
Bank Sta=252.2,267.2
XS Rating Curve= 0 ,0
Exp/Cntr=0.3,0.1

Type RM Length L Ch R = 1 ,18995.6 ,345.6,348.5,350.7
XS GIS Cut Line= 3
     2369345.602      300877.407      2369347.04      300248.092
     2369642.472       299704.74
#Sta/Elev= 30
       0  630.81   163.3  629.33   314.7  624.72   362.4  624.84  382.44623.5086
   385.5   623.4  395.64623.3969   418.2  623.44     462  625.35  531.82625.4595
  547.75625.5846  577.27626.1635  634.98 628.053   677.2  629.82  701.02629.3229
  763.84628.1806   800.9  628.72   832.8  624.62  928.54623.1488   956.5  623.47
   980.4  622.58 1003.08623.3186  1016.4  626.78  1032.3   625.5  1060.2  627.94
  1116.1  628.27    1152  630.42    1180  629.73  1211.9  626.76  1247.8  627.35
#Mann= 12 ,-1 , 0
       0     .06       0  382.44     .12       0   385.5    .045       0
  395.64     .12       0  531.82     .06       0  547.75     .08       0
  577.27     .06       0  634.98     .12       0  701.02    .016       0
  763.84     .12       0  928.54     .06       0 1003.08     .12       0
#XS Ineff= 2 , 0
           361.2  626.21
Permanent Ineff=
       F       F
Bank Sta=385.5,395.64
XS Rating Curve= 0 ,0
Exp/Cntr=0.3,0.1