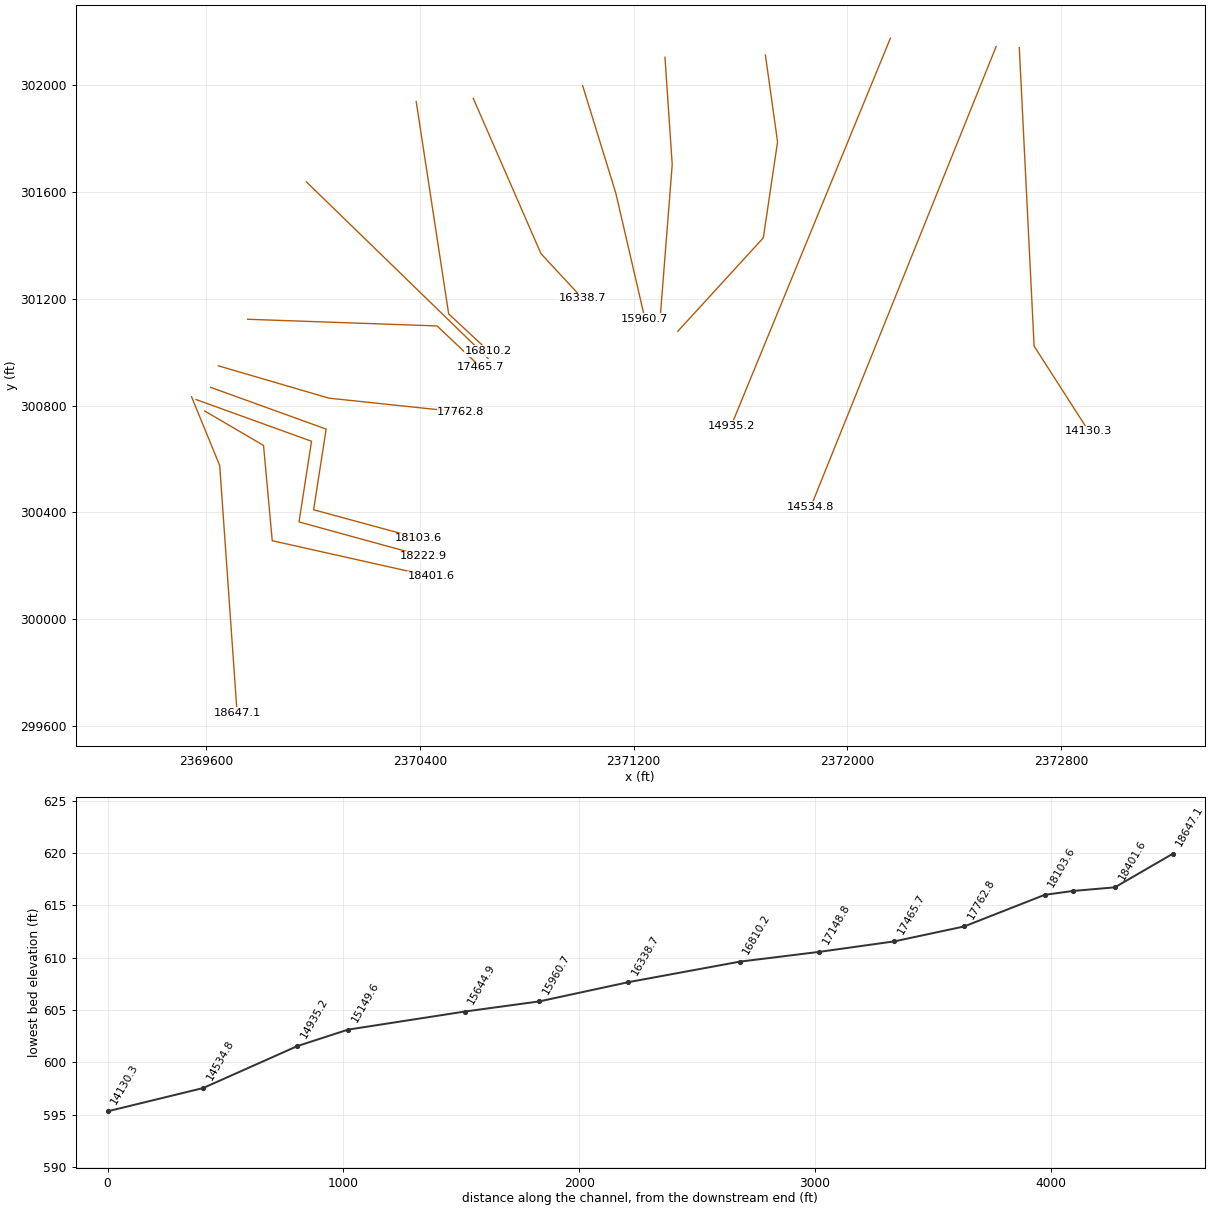
HEC-RAS study SYLVANRUN.prj: SYLVANRUN

--- SYLVANRUN.g01 (geometry) --- (continued)

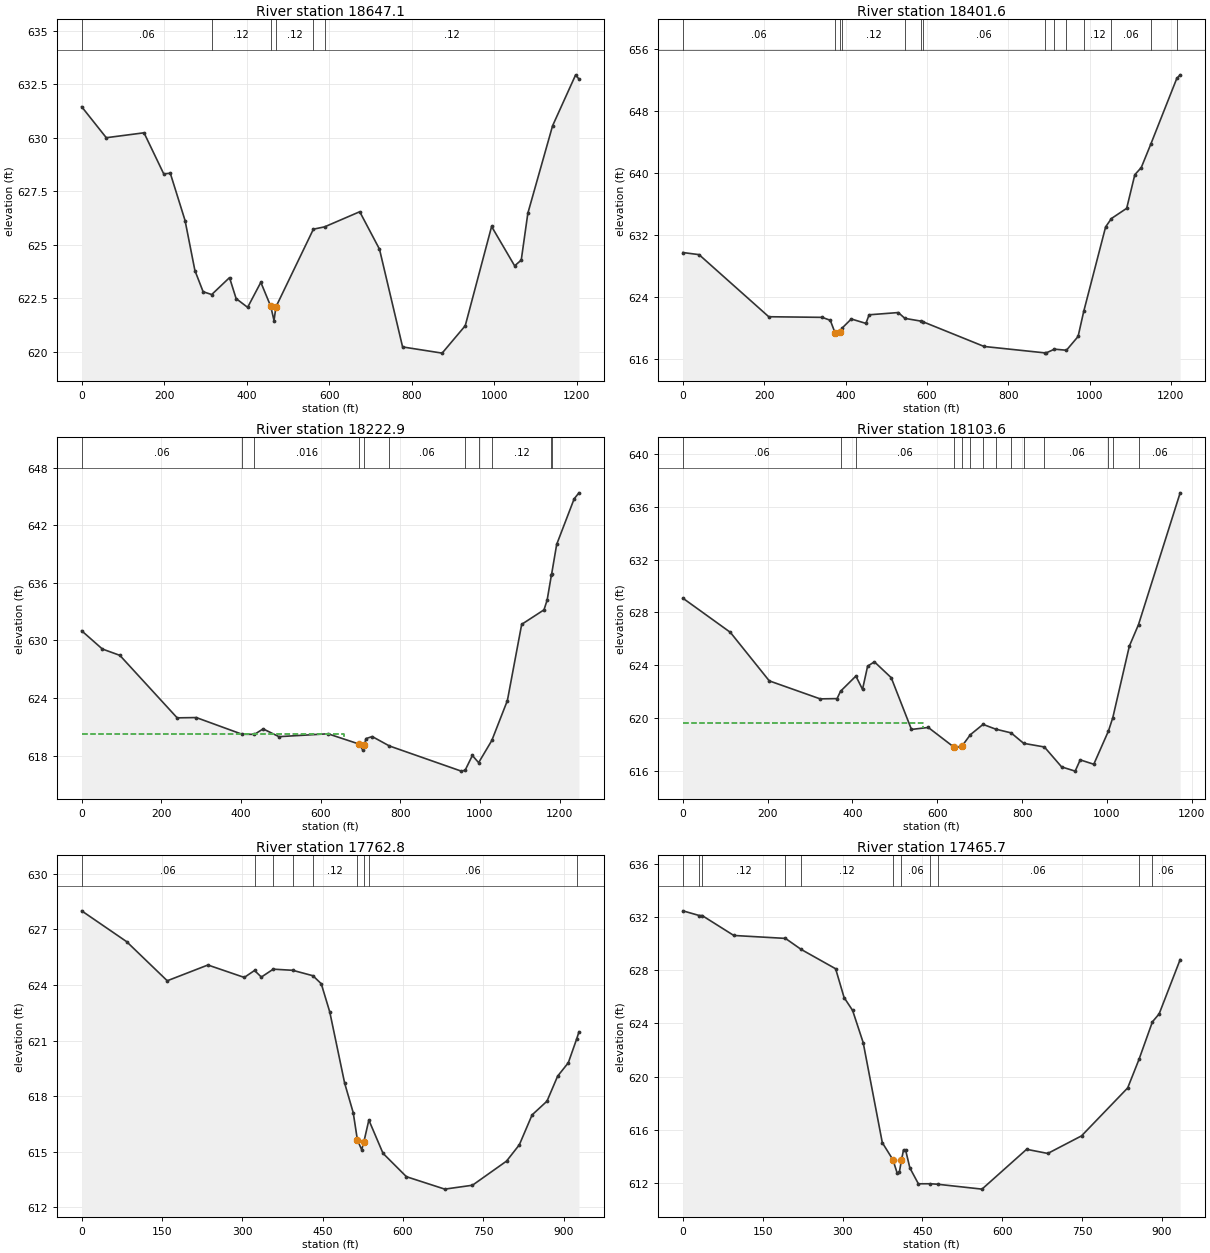
Type RM Length L Ch R = 1 ,18647.1 ,245.7,245.5,249
XS GIS Cut Line= 3
     2369544.957      300832.727     2369650.426      300574.915
     2369715.389      299650.053
#Sta/Elev= 30
       0  631.46    59.7  630.01   151.2  630.24     199  628.32   214.9  628.35
   250.7  626.14   274.6   623.8   294.5  622.81  315.34622.6789   358.5  623.47
   374.5  622.49   402.4  622.08   434.4  623.25   458.4  622.13   466.4  621.46
     471   622.1  561.84 625.734  588.98625.8428   674.2  626.55   722.1   624.8
   778.1  620.23     874  619.94     930  621.22   993.9  625.86  1049.8  624.02
  1065.8  624.29  1081.8  626.48  1141.8  630.57  1197.7  632.95  1205.7  632.75
#Mann= 6 ,-1 , 0
       0     .06       0  315.34     .12       0   458.4    .045       0
     471     .12       0  561.84    .016       0  588.98     .12       0
Bank Sta=458.4,471
XS Rating Curve= 0 ,0
Exp/Cntr=0.3,0.1

Type RM Length L Ch R = 1 ,18401.6 ,199.4,178.7,168.6
XS GIS Cut Line= 4
     2369594.436      300779.342     2369814.488      300650.436
      2369847.04      300293.665     2370441.951       300160.47
#Sta/Elev= 30
       0  629.72    39.8  629.45   211.2  621.43   342.6  621.35   362.5  620.97
   374.4  619.33   386.4  619.46  391.08619.9371   414.2  621.14   450.1  620.57
     458  621.68   529.7  621.97  546.07621.2177   586.1620.8577  591.08620.7664
   740.8  617.59  891.08 616.758   892.2  616.73  913.81617.2402  943.29617.1035
   971.9  618.88   985.7622.1065  1039.6  633.03  1053.9634.1143  1091.4  635.43
  1111.4  639.77  1127.3   640.7  1151.3643.7988 1214.53652.1984  1222.9  652.67
#Mann= 14 ,-1 , 0
       0     .06       0   374.4    .045       0   386.4     .06       0
  391.08     .12       0  546.07    .016       0   586.1     .12       0
  591.08     .06       0  891.08    .016       0  913.81     .12       0
  943.29     .06       0   985.7     .12       0  1053.9     .06       0
  1151.3     .12       0 1214.53    .016       0
Bank Sta=374.4,386.4
XS Rating Curve= 0 ,0
Exp/Cntr=0.3,0.1

Type RM Length L Ch R = 1 ,18222.9 ,119.8,119.2,87
XS GIS Cut Line= 4
     2369561.884      300822.311     2369994.176      300666.061
     2369947.301      300363.977     2370413.305       300235.99
#Sta/Elev= 30
       0     631      52   629.1    95.9  628.44   239.8  621.93   287.8  621.96
  402.67620.2225  433.87620.2095   455.7  620.78   495.4  619.97   618.5  620.27
   697.3  619.19   705.8  618.59   709.8   619.1   713.8  619.77   729.6  619.98
  772.78     619   953.1  616.38  962.84616.4717     981  618.01  996.73617.2623
 1029.81619.5728  1068.9  623.73  1104.8  631.67  1160.8  633.18  1168.7  634.19
 1179.58636.8412 1180.22636.9548  1192.7     640  1236.6  644.75  1248.6  645.37
#Mann= 11 ,-1 , 0
       0     .06       0  402.67     .12       0  433.87    .016       0
   697.3    .045       0   709.8    .016       0  772.78     .06       0
  962.84    .016       0  996.73     .06       0 1029.81     .12       0
 1179.58     .06       0 1180.22     .12       0
#XS Ineff= 2 , 0
          658.56  620.23
Permanent Ineff=
       F       F
Bank Sta=697.3,709.8
XS Rating Curve= 0 ,0
Exp/Cntr=0.3,0.1

Type RM Length L Ch R = 1 ,18103.6 ,281.9,340.8,411.3
XS GIS Cut Line= 4
     2369616.572      300867.884     2370048.863      300711.634
     2370001.988       300409.55     2370395.218      300302.779
#Sta/Elev= 30
       0  629.08   111.9   626.5   203.8  622.83   323.8  621.47   363.7  621.49
  371.81622.0449  408.06623.1935   423.7  622.19   435.7  623.94   451.7  624.27
   491.4  623.07   539.1  619.16   578.8  619.31  640.23617.8004   658.2   617.9
  678.14618.7663  707.94619.5416  737.74619.1829   774.1618.9008   803.7  618.11
  852.65617.8345   893.2  616.33   925.2  616.01   937.1  616.86   969.1  616.53
  1003.7 619.044 1013.98620.0544    1053  625.46 1074.57627.0838  1172.8  637.04
#Mann= 14 ,-1 , 0
       0     .06       0  371.81    .016       0  408.06     .06       0
  640.23    .045       0   658.2     .06       0  678.14     .12       0
  707.94     .08       0  737.74     .06       0   774.1    .016       0
   803.7     .08       0  852.65     .06       0  1003.7     .12       0
 1013.98    .016       0 1074.57     .06       0
#XS Ineff= 2 , 0
          567.18  619.65
Permanent Ineff=
       F       F
Bank Sta=640.23,658.2
XS Rating Curve= 0 ,0
Exp/Cntr=0.3,0.1

Type RM Length L Ch R = 1 ,17762.8 ,294.8,297.1,298.5
XS GIS Cut Line= 3
     2369645.218      300948.613      2370059.28      300827.519
       2370553.5      300775.258
#Sta/Elev= 30
       0  627.99    83.9  626.33   159.8  624.22   235.7  625.07   303.6   624.4
  322.73624.7744   335.5  624.42  357.71624.8458  394.06624.7844  431.75624.4916
   447.3  624.06   463.2  622.54     491   618.7     507  617.11   514.8  615.64
   522.8  615.11   526.8  615.53  536.16616.7124   562.6  614.92   606.3  613.66
   677.9  612.99   729.6   613.2   793.2   614.5   817.1  615.38   840.9  616.99
   868.7  617.73   888.6  619.08   908.5   619.8  923.92621.0644   928.4  621.47
#Mann= 9 ,-1 , 0
       0     .06       0  322.73    .016       0  357.71     .12       0
  394.06     .06       0  431.75     .12       0   514.8    .045       0
   526.8     .12       0  536.16     .06       0  923.92     .12       0
Bank Sta=514.8,526.8
XS Rating Curve= 0 ,0
Exp/Cntr=0.3,0.1

Type RM Length L Ch R = 1 ,17465.7 ,333.9,316.9,299.8
XS GIS Cut Line= 3
     2369755.084      301122.939     2370464.173       301097.97
     2370627.368      300943.456
#Sta/Elev= 30
       0  632.46   30.95632.1058   36.13632.1079    95.7  630.61  192.72 630.389
  222.24629.5624     287  628.11   302.9  625.95   318.9  624.98   338.8  622.56
   374.7  615.05   394.6  613.77   402.6  612.77   406.6  612.81   410.6  613.71
   414.6  614.52   418.5  614.49   426.5  613.15   442.5  611.96  464.95611.9636
  478.43611.9277     562  611.56   645.8  614.55   685.6  614.24     749  615.56
   835.7  619.16  857.01621.3074  882.19624.1252   894.8  624.72   934.3   628.8
#Mann= 11 ,-1 , 0
       0     .12       0   30.95     .06       0   36.13     .12       0
  192.72    .016       0  222.24     .12       0   394.6    .045       0
   410.6     .06       0  464.95     .12       0  478.43     .06       0
  857.01     .12       0  882.19     .06       0
Bank Sta=394.6,410.6
XS Rating Curve= 0 ,0
Exp/Cntr=0.3,0.1

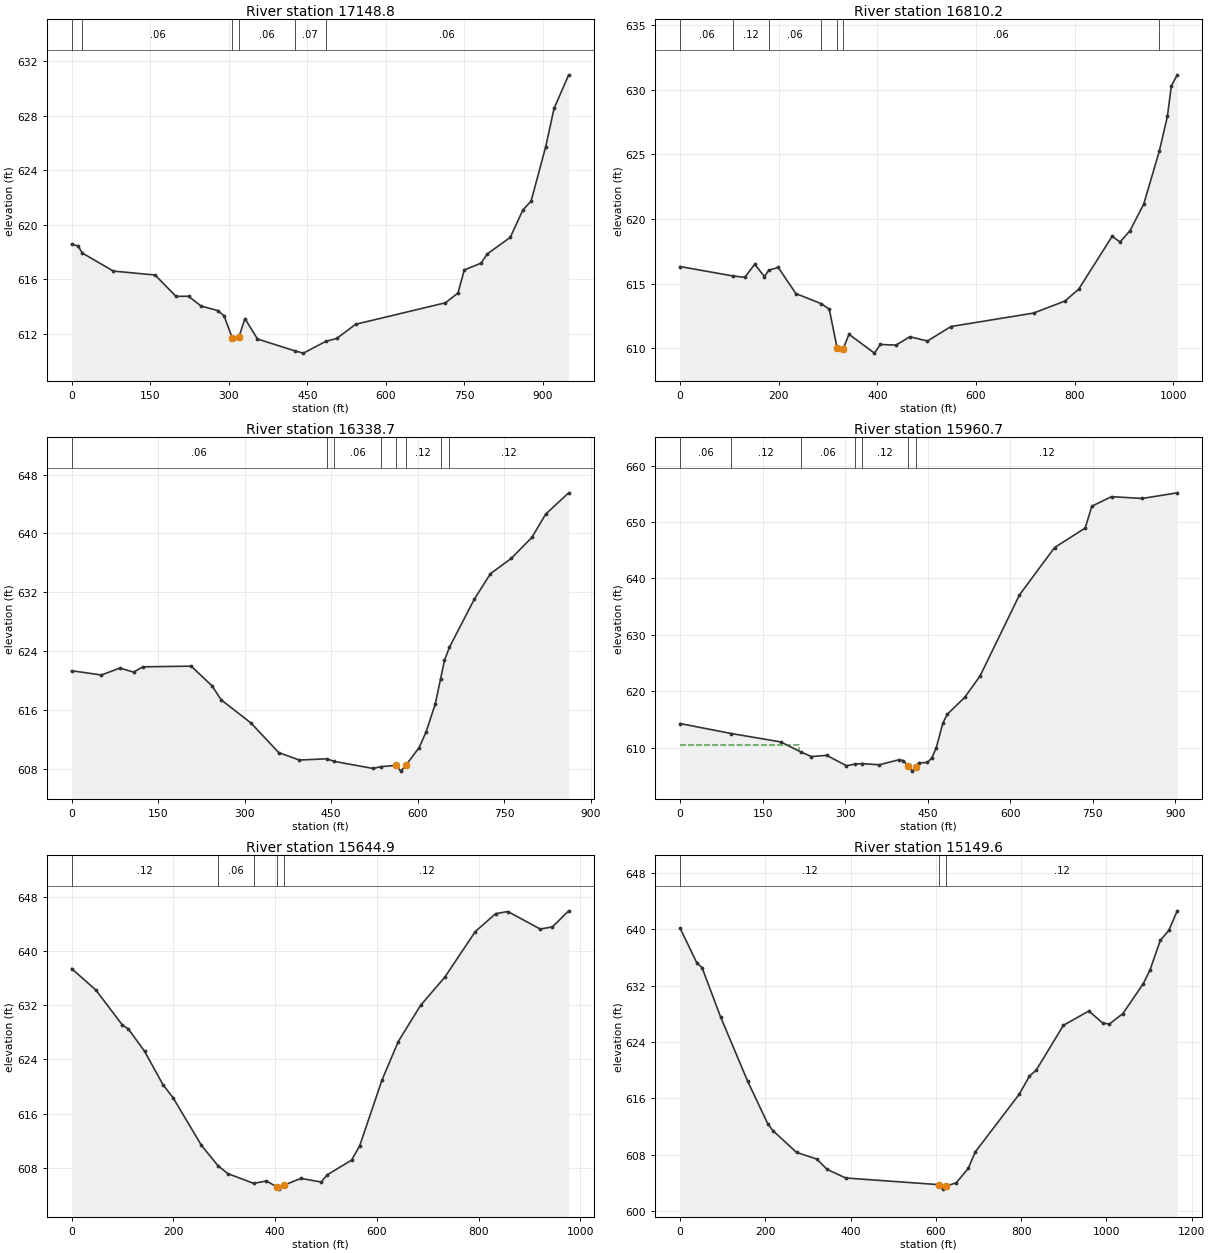
Type RM Length L Ch R = 1 ,17148.8 ,353.1,338.7,326.7
XS GIS Cut Line= 2
      2369974.59        301637.9     2370655.146      300976.442
#Sta/Elev= 30
       0  618.55      12  618.45    20.7 617.914    79.8  616.59   159.5   616.3
   199.4  614.73   223.3  614.74   247.2  614.02   279.1  613.69   291.1  613.31
     307  611.65   319.5  611.74     331   613.1   354.9   611.6  425.87610.7308
   442.6  610.56  485.42611.4249   506.4  611.64   542.3  612.68   713.8  614.26
   737.7  614.98   749.7  616.67   781.6  617.17   793.5  617.85   837.4  619.06
   861.3  621.06   877.3  621.74   905.2  625.74   921.1  628.54     949  631.01
#Mann= 6 ,-1 , 0
       0     .12       0    20.7     .06       0     307    .045       0
   319.5     .06       0  425.87     .07       0  485.42     .06       0
Bank Sta=307,319.5
XS Rating Curve= 0 ,0
Exp/Cntr=0.3,0.1

Type RM Length L Ch R = 1 ,16810.2 ,466.9,471.5,474.7
XS GIS Cut Line= 3
     2370386.048      301938.247     2370507.576      301143.109
     2370656.882       301004.22
#Sta/Elev= 30
       0  616.32  107.49615.5899   131.4  615.49   151.3   616.5   171.2  615.54
  179.62616.0373   199.1  616.25   234.9  614.23  286.58613.4427   302.6  613.02
   318.6  609.99   330.5  609.92   342.5  611.08   394.2  609.62   406.2  610.29
     438  610.24   465.9  610.89   501.7  610.56   549.5  611.68   716.8  612.72
   780.5  613.65   808.4  614.57   876.3  618.66   892.3  618.22   912.3  619.09
   940.3  621.15  971.98625.2696   988.3  627.94   996.3   630.3  1008.3  631.16
#Mann= 7 ,-1 , 0
       0     .06       0  107.49     .12       0  179.62     .06       0
  286.58     .12       0   318.6    .045       0   330.5     .06       0
  971.98     .12       0
Bank Sta=318.6,330.5
XS Rating Curve= 0 ,0
Exp/Cntr=0.3,0.1

Type RM Length L Ch R = 1 ,16338.7 ,375.7,378,375.5
XS GIS Cut Line= 3
      2370599.59        301950.4     2370853.062      301368.803
     2371007.576      301202.136
#Sta/Elev= 30
       0  621.32    51.9  620.74    83.8  621.68   107.7  621.13   123.7  621.85
   207.5  621.94   243.4  619.27   259.4  617.36   311.2   614.2   359.1  610.18
     395  609.17  442.38609.3352   455.2608.9885   522.7  608.02  536.14 608.268
   562.6  608.44   570.6  607.66   579.9608.5005   602.5  610.87   614.5  612.98
   630.4  616.78  639.63 620.195   646.4  622.72  655.05624.5235   698.2  631.06
   726.1  634.52     762  636.59   797.9  639.45   821.8  642.62   861.7  645.52
#Mann= 8 ,-1 , 0
       0     .06       0  442.38     .07       0   455.2     .06       0
  536.14     .12       0   562.6    .045       0   579.9     .12       0
  639.63     .06       0  655.05     .12       0
Bank Sta=562.6,579.9
XS Rating Curve= 0 ,0
Exp/Cntr=0.3,0.1

Type RM Length L Ch R = 1 ,15960.7 ,294.2,315.8,262.7
XS GIS Cut Line= 3
     2371009.303      301997.552     2371133.595      301594.484
     2371242.298      301124.879
#Sta/Elev= 30
       0  614.26   93.21612.4858     183     611  219.48609.2203   238.8   608.4
   266.6  608.62   302.4  606.78  317.56607.0586  331.09  607.16   362.1  606.94
   397.9  607.84   405.9  607.69   414.3  606.76   421.8  605.82   429.3   606.6
   433.8  607.29   449.7  607.35   457.6  608.16   465.6  609.93   477.6  614.31
   485.5  615.88   517.4   618.9   545.3  622.69     617  637.07   680.7  645.46
   736.5  648.93   748.5   652.8   784.3  654.49   840.1  654.17   903.8  655.17
#Mann= 7 ,-1 , 0
       0     .06       0   93.21     .12       0  219.48     .06       0
  317.56     .07       0  331.09     .12       0   414.3    .045       0
   429.3     .12       0
#XS Ineff= 2 , 0
          215.69  610.54
Permanent Ineff=
       F       F
Bank Sta=414.3,429.3
XS Rating Curve= 0 ,0
Exp/Cntr=0.3,0.1

Type RM Length L Ch R = 1 ,15644.9 ,471,495.3,502.3
XS GIS Cut Line= 3
     2371317.398      302104.173     2371344.521      301702.251
      2371299.59      301130.088
#Sta/Elev= 30
       0  637.38    47.9  634.21    99.7  629.07   111.7  628.47   143.6  625.17
   179.5  620.27   199.4  618.34   255.3   611.3  288.22608.2588   307.1  607.14
  357.73605.7009   382.9  606.05   402.8  605.21   406.8  604.85   417.8  605.44
   450.7  606.43   490.5   605.9   502.5  606.96   550.3  609.13   566.2  611.25
   610.1  620.96     642  626.62   685.8  631.95   733.6  636.13   793.4  642.84
   833.3  645.47   857.2  645.79     921   643.2   944.9  643.53   976.8  645.89
#Mann= 5 ,-1 , 0
       0     .12       0  288.22     .06       0  357.73     .12       0
   402.8    .045       0   417.8     .12       0
Bank Sta=402.8,417.8
XS Rating Curve= 0 ,0
Exp/Cntr=0.3,0.1

Type RM Length L Ch R = 1 ,15149.6 ,219.3,214.4,207.8
XS GIS Cut Line= 4
     2371693.395      302112.675     2371738.968      301787.154
     2371685.582      301427.779     2371365.562      301078.004
#Sta/Elev= 30
       0  640.16    39.6   635.2    51.5  634.56      95  627.56   158.4  618.45
   205.9  612.37   217.8  611.42   273.2  608.33   320.8  607.39   344.7  605.92
   388.6   604.7   608.2  603.75   616.2  603.12   624.1  603.54   648.1  604.04
     676  606.07     692  608.37   795.6   616.6   819.5  619.17   835.4  620.01
   899.2  626.38   958.9   628.4   990.8  626.72  1006.7  626.54  1038.6  628.04
  1086.4  632.28  1102.4  634.25  1126.3  638.42  1146.2  639.83  1166.1  642.62
#Mann= 3 ,-1 , 0
       0     .12       0   608.2    .045       0   624.1     .12       0
Bank Sta=608.2,624.1
XS Rating Curve= 0 ,0
Exp/Cntr=0.3,0.1

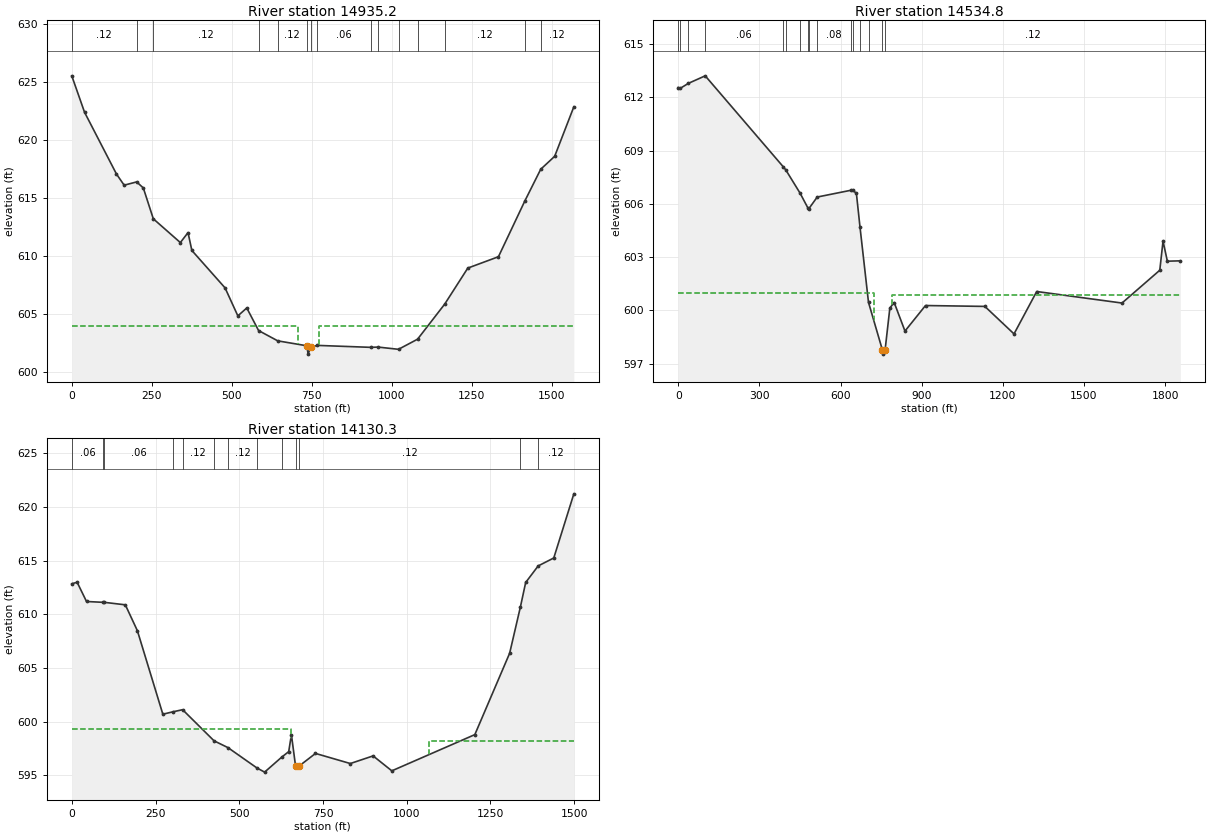
Type RM Length L Ch R = 1 ,14935.2 ,400.8,400.4,400.6
XS GIS Cut Line= 2
     2372161.277      302175.175     2371565.215      300723.838
#Sta/Elev= 30
       0  625.55    39.9  622.41   139.7  617.08   163.7  616.12  202.82 616.401
   223.6  615.88  254.83613.2202   339.3  611.17   363.3  612.03   375.3  610.49
   479.1  607.26     519  604.85   546.9  605.53  583.79603.5833  643.68602.6944
   734.6  602.27   738.6  601.55   746.4  602.15  767.59602.3027  934.66602.1346
  957.34602.1572 1021.04601.9656 1080.64602.8385 1165.47605.8652  1237.6  608.97
  1333.4  609.95 1416.09614.7729 1465.45617.4918  1509.1  618.61    1569  622.88
#Mann= 15 ,-1 , 0
       0     .12       0  202.82    .016       0  254.83     .12       0
  583.79     .06       0  643.68     .12       0   734.6    .045       0
   746.4     .12       0  767.59     .06       0  934.66     .12       0
  957.34     .06       0 1021.04     .12       0 1080.64     .06       0
 1165.47     .12       0 1416.09    .016       0 1465.45     .12       0
#XS Ineff= 2 , 0
          708.36     604  772.76             604
Permanent Ineff=
       F       F
Bank Sta=734.6,746.4
XS Rating Curve= 0 ,0
Exp/Cntr=0.3,0.1

Type RM Length L Ch R = 1 ,14534.8 ,394.2,404.5,414.3
XS GIS Cut Line= 2
      2372557.11      302143.925     2371863.826      300421.754
#Sta/Elev= 30
       0  612.56     8.1 612.521   37.74612.7976   99.75613.2205  387.43608.1078
   397.6 607.918  450.65606.6021  480.03605.7537  482.26605.7147  513.87606.3862
  640.31606.7738  644.88606.7852   658.8  606.59  671.93604.7178  703.54 600.448
   754.6  597.78   758.6  597.53     765  597.78   782.5  600.13   798.5  600.44
   838.4  598.83   914.3  600.27  1133.8  600.22  1241.6  598.67  1325.5  601.06
  1640.9  600.41  1780.6  602.26  1792.6   603.9  1808.6  602.77  1856.5  602.79
#Mann= 16 ,-1 , 0
       0     .08       0     8.1     .12       0   37.74     .08       0
   99.75     .06       0  387.43     .12       0   397.6     .06       0
  450.65     .12       0  480.03     .06       0  482.26     .12       0
  513.87     .08       0  640.31     .06       0  644.88     .08       0
  671.93     .06       0  703.54     .12       0   754.6    .045       0
     765     .12       0
#XS Ineff= 2 , 0
          724.46  600.96  790.51          600.86
Permanent Ineff=
       F       F
Bank Sta=754.6,765
XS Rating Curve= 0 ,0
Exp/Cntr=0.3,0.1

Type RM Length L Ch R = 1 ,14130.3 ,319.7,320,318.5
XS GIS Cut Line= 3
     2372643.915      302140.453     2372699.471      301022.398
     2372904.332      300702.953
#Sta/Elev= 30
       0  612.84      16  612.98      44  611.19   94.27611.1113   97.08611.1119
   159.9  610.88   195.9  608.47   271.9   600.7  301.33600.9185  330.91  601.12
  424.78598.2231  466.33597.5904  552.72595.6998   575.7  595.31  626.21  596.69
   647.7  597.22   655.7   598.8     668   595.9   679.7   595.9   727.6  597.05
   831.6  596.11   899.6  596.82   955.5  595.43  1203.3   598.8  1307.2  606.37
 1339.54610.7083  1355.1  612.96 1392.41614.5004    1439  615.24  1498.9  621.21
#Mann= 13 ,-1 , 0
       0     .06       0   94.27     .08       0   97.08     .06       0
  301.33     .08       0  330.91     .12       0  424.78     .06       0
  466.33     .12       0  552.72     .06       0  626.21     .12       0
     668    .045       0   679.7     .12       0 1339.54     .06       0
 1392.41     .12       0
#XS Ineff= 2 , 0
          653.87  599.31 1066.67          598.24
Permanent Ineff=
       F       F
Bank Sta=668,679.7
XS Rating Curve= 0 ,0
Exp/Cntr=0.3,0.1