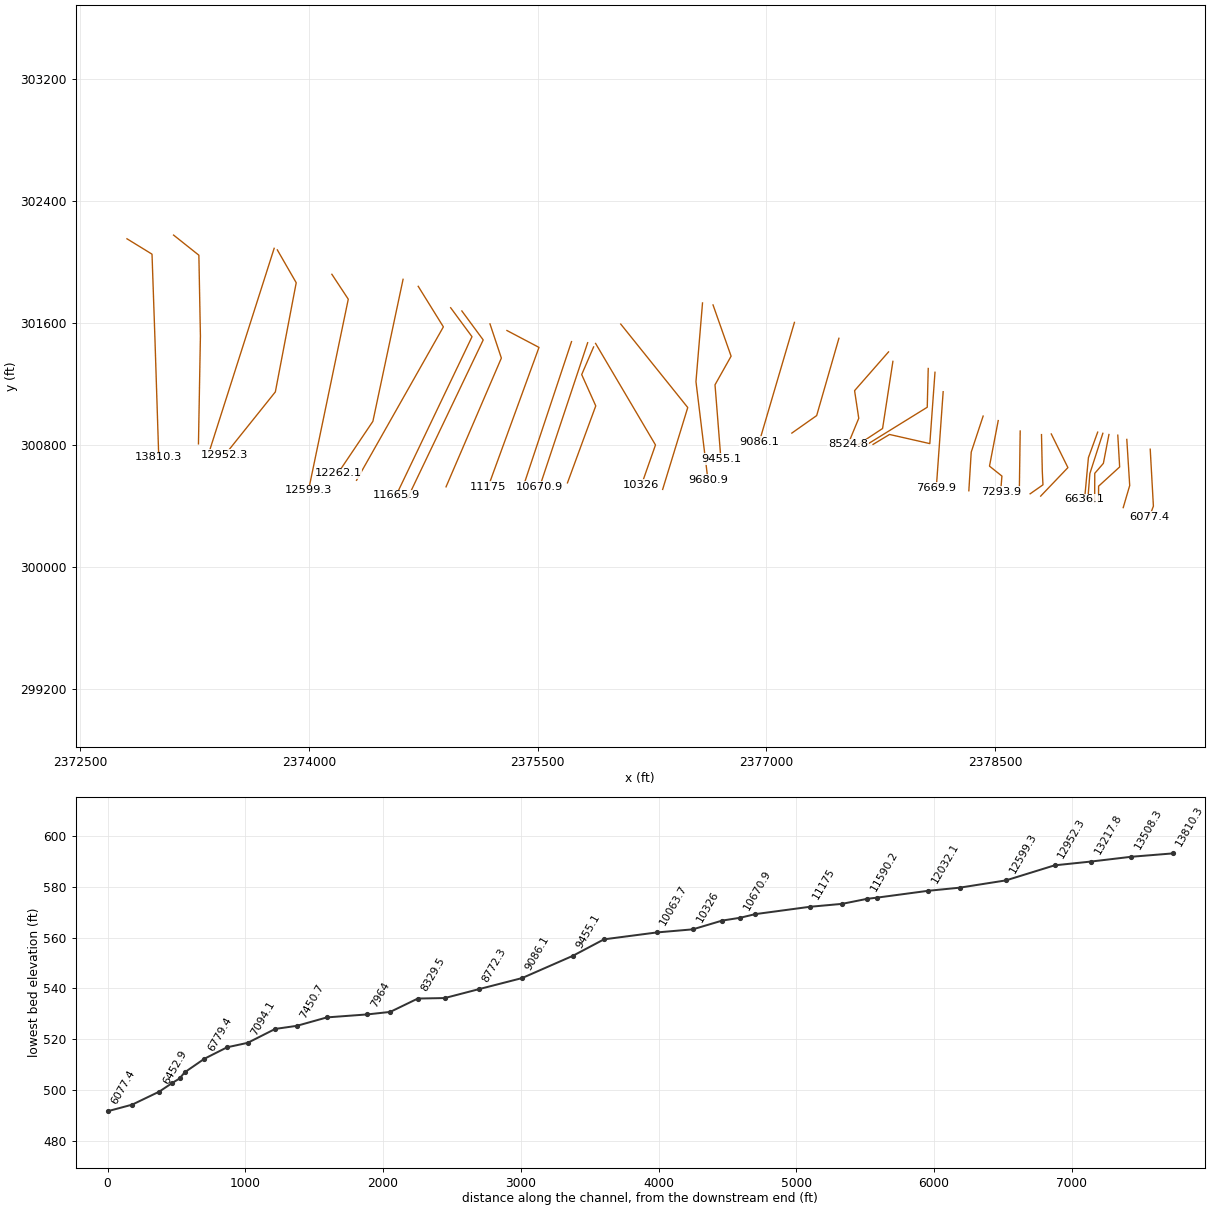
HEC-RAS study SYLVANRUN.prj: SYLVANRUN

--- SYLVANRUN.g01 (geometry) --- (continued)

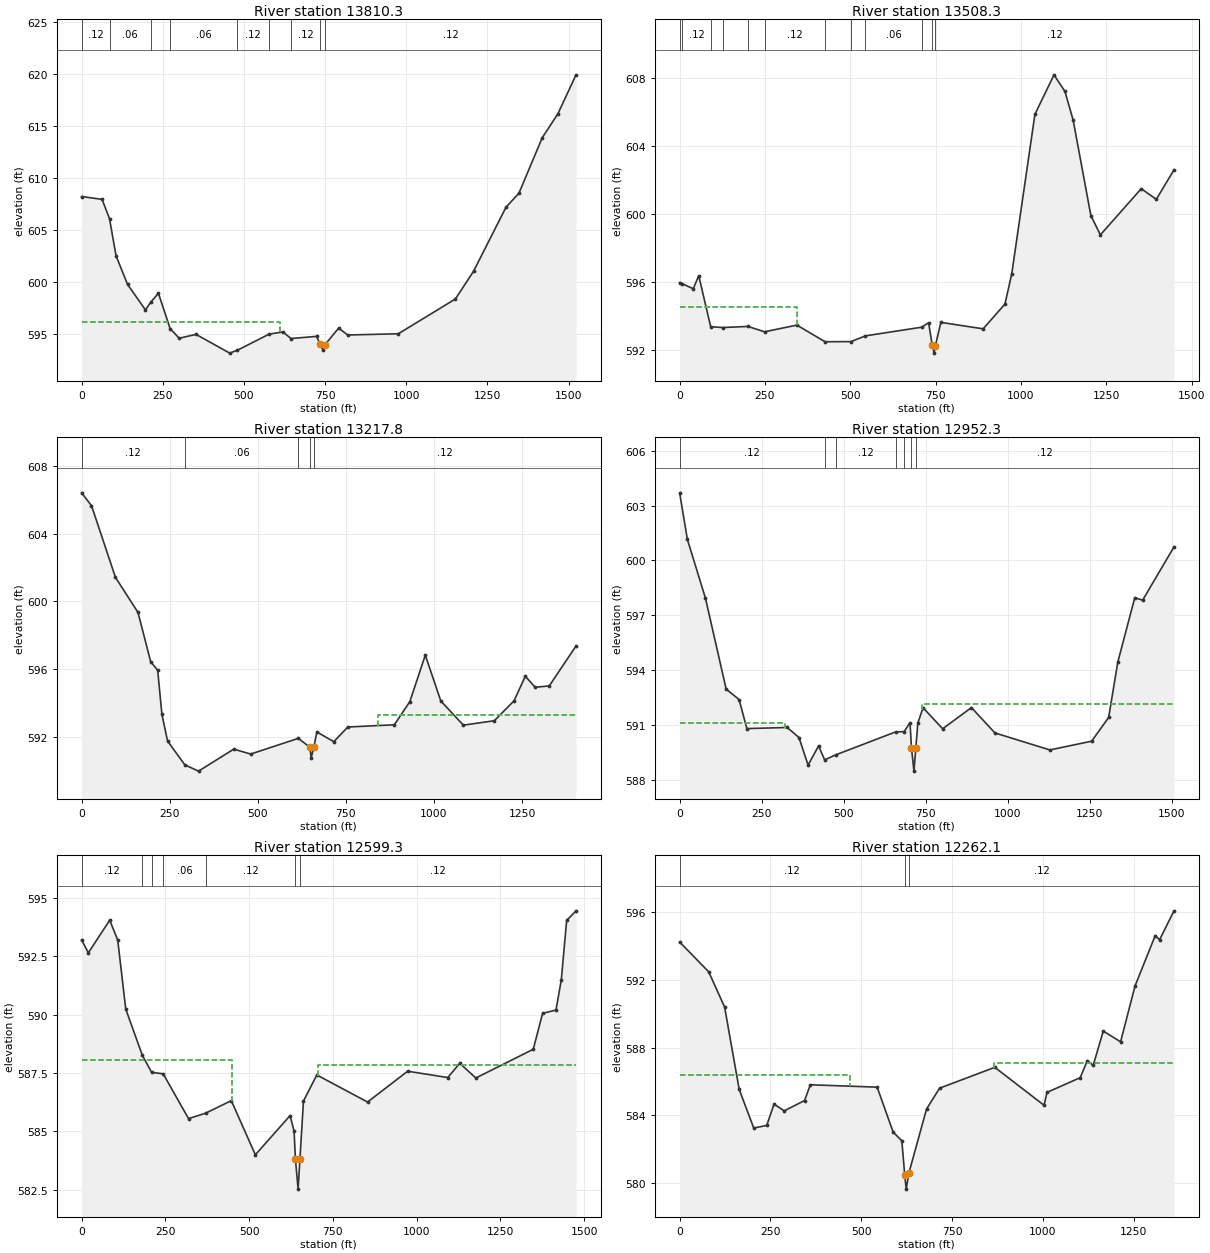
Type RM Length L Ch R = 1 ,13810.3 ,303,302,300.8
XS GIS Cut Line= 4
      2372807.11       302150.87     2372971.268      302050.089
     2372990.602      301491.156     2373015.443      300720.314
#Sta/Elev= 30
       0   608.2    62.9  607.93   85.89606.0776   106.1   602.5   141.5  599.76
   196.6  597.31  212.71598.0466   236.6  598.91  272.46595.5228   300.5  594.59
   352.4  594.96   456.3  593.16  479.99593.4374  577.73594.9867   620.1  595.19
   645.1594.5627   723.9  594.77   734.5  594.03   743.9  593.44   749.5  593.96
   791.8  595.56   819.8   594.9   975.7  595.02  1151.5  598.36  1207.4  601.02
  1307.4  607.17  1347.3  608.52  1419.2  613.86  1467.2  616.14  1523.1  619.89
#Mann= 9 ,-1 , 0
       0     .12       0   85.89     .06       0  212.71     .12       0
  272.46     .06       0  479.99     .12       0  577.73     .06       0
   645.1     .12       0   734.5    .045       0   749.5     .12       0
#XS Ineff= 2 , 0
          610.94  596.18
Permanent Ineff=
       F       F
Bank Sta=734.5,749.5
XS Rating Curve= 0 ,0
Exp/Cntr=0.3,0.1

Type RM Length L Ch R = 1 ,13508.3 ,297.8,290.5,283.9
XS GIS Cut Line= 4
     2373112.665      302175.175     2373278.582      302043.217
     2373288.701      301513.926      2373275.86       300807.12
#Sta/Elev= 30
       0  595.98    7.33 595.915      40  595.62      56  596.39   90.95 593.385
  126.14593.3361  200.04593.4006  248.85593.0853   343.4  593.48  426.05592.5009
  502.22592.5085   544.2592.8454  709.18593.3567   729.4  593.62  739.65592.3375
   745.4  591.83   748.9  592.24   765.3  593.64   889.2  593.26   953.1  594.72
     973   596.5  1040.9  605.89  1096.8  608.21  1128.8  607.23  1152.8  605.55
  1204.7  599.93  1232.6  598.79  1352.4  601.51  1396.4  600.88  1448.3  602.62
#Mann= 12 ,-1 , 0
       0     .06       0    7.33     .12       0   90.95     .06       0
  126.14     .12       0  200.04     .06       0  248.85     .12       0
  426.05     .06       0  502.22     .12       0   544.2     .06       0
  709.18     .12       0  739.65    .045       0   748.9     .12       0
#XS Ineff= 2 , 0
          343.45  594.56
Permanent Ineff=
       F       F
Bank Sta=739.65,748.9
XS Rating Curve= 0 ,0
Exp/Cntr=0.3,0.1

Type RM Length L Ch R = 1 ,13217.8 ,262.7,265.5,267.6
XS GIS Cut Line= 2
     2373772.388       302088.37      2373345.25      300751.615
#Sta/Elev= 30
       0  606.42      28  605.66      96  601.42   159.9  599.35   195.9  596.44
   215.9  595.92   227.9  593.31   243.9  591.74  292.97590.3306   331.8  589.96
   431.8  591.26   479.8  590.97  615.42591.9009   647.7  591.37   651.7  590.76
   659.5  591.41   667.7  592.28   715.7   591.7   755.6  592.57   887.6   592.7
   931.6  594.07   975.5  596.82  1019.5  594.11  1083.5  592.68  1171.4  592.94
  1227.4  594.12  1259.4  595.57  1287.4  594.92  1327.4     595  1403.3  597.36
#Mann= 5 ,-1 , 0
       0     .12       0  292.97     .06       0  615.42     .12       0
   647.7    .045       0   659.5     .12       0
#XS Ineff= 2 , 0
                          842.11           593.3
Permanent Ineff=
       F       F
Bank Sta=647.7,659.5
XS Rating Curve= 0 ,0
Exp/Cntr=0.3,0.1

Type RM Length L Ch R = 1 ,12952.3 ,352.8,353,352.8
XS GIS Cut Line= 4
     2373793.221      302077.953     2373917.052      301862.902
     2373780.146      301147.449     2373448.896      300734.254
#Sta/Elev= 30
       0   603.7    23.6  601.15    78.8  597.92   141.8  592.95   181.2  592.38
   204.8  590.79   327.8  590.85   363.6   590.3   391.4  588.79   423.3  589.84
  441.83589.0754  475.68589.3515  658.12590.6078  683.83590.6229   701.9  591.11
  706.35589.7404   713.9  588.46  719.68589.7527   725.8   591.1   741.7  591.93
   801.4  590.78     889  591.94   960.7  590.55  1127.9  589.62  1255.3   590.1
  1307.1   591.4    1335  594.43  1386.7  597.96  1410.6  597.82  1506.2  600.74
#Mann= 7 ,-1 , 0
       0     .12       0  441.83     .06       0  475.68     .12       0
  658.12     .06       0  683.83     .12       0  706.35    .045       0
  719.68     .12       0
#XS Ineff= 2 , 0
          321.98  591.08  739.73          592.11
Permanent Ineff=
       F       F
Bank Sta=706.35,719.68
XS Rating Curve= 0 ,0
Exp/Cntr=0.3,0.1

Type RM Length L Ch R = 1 ,12599.3 ,336.6,337.2,343.7
XS GIS Cut Line= 3
      2374150.86      301918.231     2374258.499      301755.036
     2373997.507      300501.615
#Sta/Elev= 30
       0  593.21      20  592.65    83.8  594.05   107.7   593.2   131.7  590.24
  181.11588.2673  208.88587.5305   243.4  587.47   319.1  585.55  369.77585.7808
   446.8  586.32   518.6     584   622.3  585.68   634.2  585.01   638.2  583.82
   646.2  582.53   651.6   583.8   662.2   586.3     702  587.42   853.6  586.26
   973.2  587.58  1092.9  587.31  1128.8  587.92  1176.7  587.29  1348.2  588.52
  1376.1  590.06    1416   590.2  1431.9  591.49  1447.9  594.04  1475.8  594.45
#Mann= 7 ,-1 , 0
       0     .12       0  181.11     .06       0  208.88     .12       0
   243.4     .06       0  369.77     .12       0   638.2    .045       0
   651.6     .12       0
#XS Ineff= 2 , 0
          449.12  588.08  705.06          587.84
Permanent Ineff=
       F       F
Bank Sta=638.2,651.6
XS Rating Curve= 0 ,0
Exp/Cntr=0.3,0.1

Type RM Length L Ch R = 1 ,12262.1 ,235.8,230.1,217.6
XS GIS Cut Line= 3
     2374617.874      301885.245     2374419.957      300954.689
     2374191.253      300615.337
#Sta/Elev= 30
       0  594.24      80  592.48   123.9  590.39   163.9  585.54   203.9  583.26
   239.8  583.41   259.8  584.67   287.8  584.27   343.8  584.88   359.8  585.81
   543.6  585.67   587.6  583.02   611.6   582.5   619.6  580.46   623.6  579.65
   630.8  580.59   679.6  584.38   715.5  585.61   867.4  586.84    1003   584.6
    1011  585.36  1102.4  586.23  1122.2  587.24  1138.1  586.95  1165.9  588.98
  1213.6  588.35  1253.3  591.64    1309  594.62  1320.9  594.37  1360.6  596.08
#Mann= 3 ,-1 , 0
       0     .12       0   619.6    .045       0   630.8     .12       0
#XS Ineff= 2 , 0
          469.56  586.38  863.98          587.12
Permanent Ineff=
       F       F
Bank Sta=619.6,630.8
XS Rating Curve= 0 ,0
Exp/Cntr=0.3,0.1

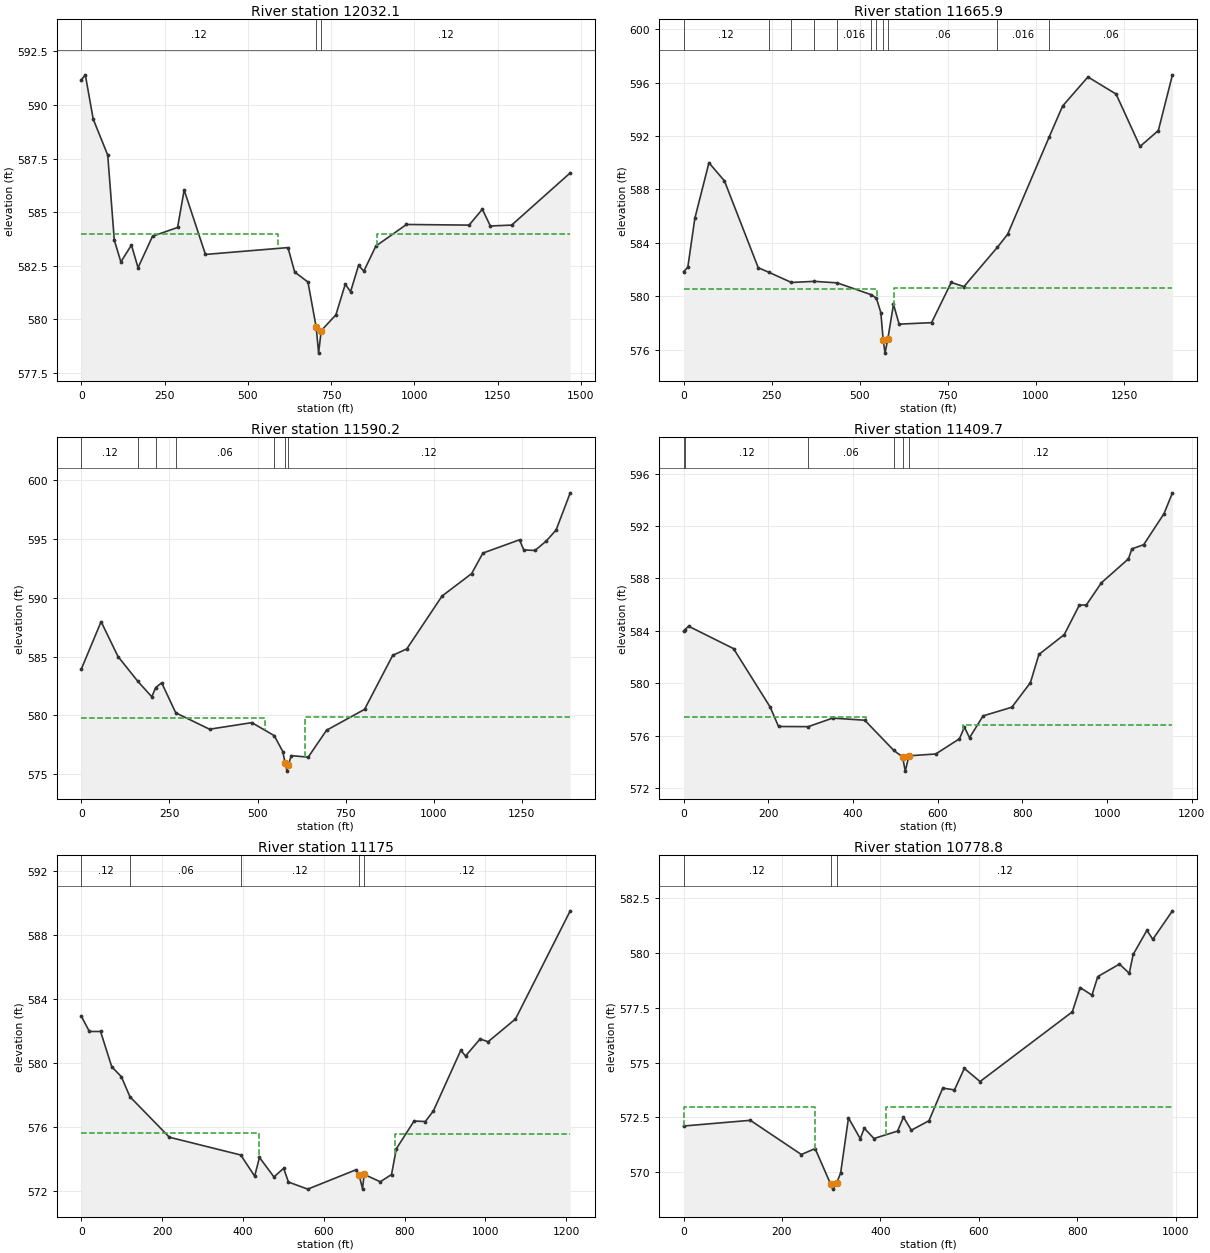
Type RM Length L Ch R = 1 ,12032.1 ,362.5,366.2,365.1
XS GIS Cut Line= 3
     2374717.295      301839.296     2374882.226      301573.671
     2374312.781      300568.462
#Sta/Elev= 30
       0  591.18    11.9  591.41    35.6  589.34    79.2  587.66    98.9  583.69
   118.7  582.67   150.4  583.46   170.2   582.4   213.7  583.87   288.9  584.28
   308.7  586.03   372.6  583.02   620.5  583.34   640.5   582.2   680.4  581.73
   705.2  579.62   712.4  578.41   720.2  579.46   764.4   580.2   792.4  581.63
   808.4  581.28   832.4  582.51   848.3  582.24   884.3  583.41   976.3  584.42
  1164.2  584.39  1204.1  585.13  1228.1  584.35  1292.1  584.39    1468  586.83
#Mann= 3 ,-1 , 0
       0     .12       0   705.2    .045       0   720.2     .12       0
#XS Ineff= 2 , 0
          591.12  583.98  886.69          583.98
Permanent Ineff=
       F       F
Bank Sta=705.2,720.2
XS Rating Curve= 0 ,0
Exp/Cntr=0.3,0.1

Type RM Length L Ch R = 1 ,11665.9 ,75.5,75.7,75.8
XS GIS Cut Line= 3
     2374930.056      301699.018     2375070.029      301509.131
     2374573.068      300470.719
#Sta/Elev= 30
       0  581.85      12  582.17      32  585.84      72     590     116  588.64
   211.9  582.14  240.98 581.813  305.91  581.04  370.85581.1219  435.79581.0098
  533.19580.1167  547.18579.8573   559.7  578.79   566.4  576.74   571.7  575.75
   579.7  576.84   595.6   579.4   611.6  577.92   703.6  578.03   759.5  581.04
   795.5  580.73  890.35583.6701   919.4  584.64 1036.77591.8914  1075.3  594.24
  1147.3  596.42  1227.2  595.14  1295.2  591.22  1347.1  592.41  1387.1  596.58
#Mann= 11 ,-1 , 0
       0     .12       0  240.98    .016       0  305.91    .016       0
  370.85    .016       0  435.79    .016       0  533.19    .016       0
  547.18     .06       0   566.4    .045       0   579.7     .06       0
  890.35    .016       0 1036.77     .06       0
#XS Ineff= 2 , 0
          547.57  580.57   596.7          580.62
Permanent Ineff=
       F       F
Bank Sta=566.4,579.7
XS Rating Curve= 0 ,0
Exp/Cntr=0.3,0.1

Type RM Length L Ch R = 1 ,11590.2 ,180.2,180.5,178.2
XS GIS Cut Line= 3
     2375003.536      301677.837      2375143.51       301487.95
     2374646.549      300449.539
#Sta/Elev= 30
       0  583.95      56  587.98     104  585.01  160.37582.8918   199.9  581.58
  210.96582.3683   227.9  582.77  267.76580.2156   363.8  578.82   483.7  579.38
  547.24578.2738   571.7  576.91   577.8  575.97   583.7  575.25   587.7  575.81
   595.6  576.57   643.6  576.44   695.6  578.73   803.5  580.51   883.4  585.11
   923.4  585.66  1023.4  590.16  1107.3  592.07  1139.3  593.82  1243.2  594.95
  1255.2  594.09  1287.2  594.04  1319.2  594.85  1347.1  595.79  1387.1  598.95
#Mann= 7 ,-1 , 0
       0     .12       0  160.37    .016       0  210.96     .12       0
  267.76     .06       0  547.24     .12       0   577.8    .045       0
   587.7     .12       0
#XS Ineff= 2 , 0
          521.57  579.81  635.71          579.86
Permanent Ineff=
       F       F
Bank Sta=577.8,587.7
XS Rating Curve= 0 ,0
Exp/Cntr=0.3,0.1

Type RM Length L Ch R = 1 ,11409.7 ,233.4,234.7,235.7
XS GIS Cut Line= 3
     2375187.926      301593.202     2375262.579      301369.244
     2374899.731      300525.494
#Sta/Elev= 30
       0  583.97     2.2 584.049    11.8  584.35     118  582.64   204.6  578.17
   224.3  576.69  294.49576.6774   351.9  577.33   427.8  577.17  496.47574.8626
   517.1  574.37   523.6  573.28   532.1  574.45   595.5  574.59   651.4  575.75
   663.4  576.64   675.3  575.83   707.3   577.5   775.2  578.16   819.1  580.04
   839.1  582.19     899  583.71   934.9  585.98   950.9  585.96   986.8  587.67
  1050.7   589.5  1058.7  590.26  1086.6  590.58  1134.6  592.95  1154.5  594.54
#Mann= 6 ,-1 , 0
       0     .06       0     2.2     .12       0  294.49     .06       0
  496.47     .12       0   517.1    .045       0   532.1     .12       0
#XS Ineff= 2 , 0
          429.72  577.39  660.06          576.84
Permanent Ineff=
       F       F
Bank Sta=517.1,532.1
XS Rating Curve= 0 ,0
Exp/Cntr=0.3,0.1

Type RM Length L Ch R = 1 ,11175   ,395.9,396.2,394.8
XS GIS Cut Line= 3
     2375299.037      301549.799     2375509.312      301439.115
     2375175.773      300525.494
#Sta/Elev= 30
       0  582.91    19.8  581.96    47.5  581.96    75.2  579.76      99  579.14
  120.21577.8877   217.8  575.36  394.55  574.25     429  572.93   440.9   574.1
   476.8  572.88   500.7  573.42   512.7  572.56   560.5  572.12   680.1  573.33
   687.6     573     696  572.14     700  573.04   739.9  572.58   767.8  573.03
   779.7  574.64   823.6  576.37   851.5  576.34   871.4     577   939.2  580.78
   951.1  580.43     987  581.49  1006.9  581.32  1074.7  582.74  1210.2  589.49
#Mann= 5 ,-1 , 0
       0     .12       0  120.21     .06       0  394.55     .12       0
   687.6    .045       0     700     .12       0
#XS Ineff= 2 , 0
          440.66  575.65   777.3          575.56
Permanent Ineff=
       F       F
Bank Sta=687.6,700
XS Rating Curve= 0 ,0
Exp/Cntr=0.3,0.1

Type RM Length L Ch R = 1 ,10778.8 ,108,107.9,107.1
XS GIS Cut Line= 2
     2375722.648      301476.882     2375408.412      300534.174
#Sta/Elev= 30
       0  572.11   135.7  572.37   239.4  570.81   267.4  571.08   299.1  569.45
   303.3  569.23   311.3  569.52   319.3  569.97   335.2  572.48   359.2  571.53
   367.2  572.01   387.1  571.54     435  571.88     447  572.52   462.9  571.92
   498.8  572.35   526.8  573.84   550.7  573.76   570.7  574.74   602.6  574.14
   790.2  577.32   806.1  578.43   830.1  578.08     842  578.93     886   579.5
   905.9  579.08   913.9  579.94   941.8  581.04   953.8  580.63   993.7  581.93
#Mann= 3 ,-1 , 0
       0     .12       0   299.1    .045       0   311.3     .12       0
#XS Ineff= 2 , 0
          266.41     573  410.73          572.99
Permanent Ineff=
       F       F
Bank Sta=299.1,311.3
XS Rating Curve= 0 ,0
Exp/Cntr=0.3,0.1

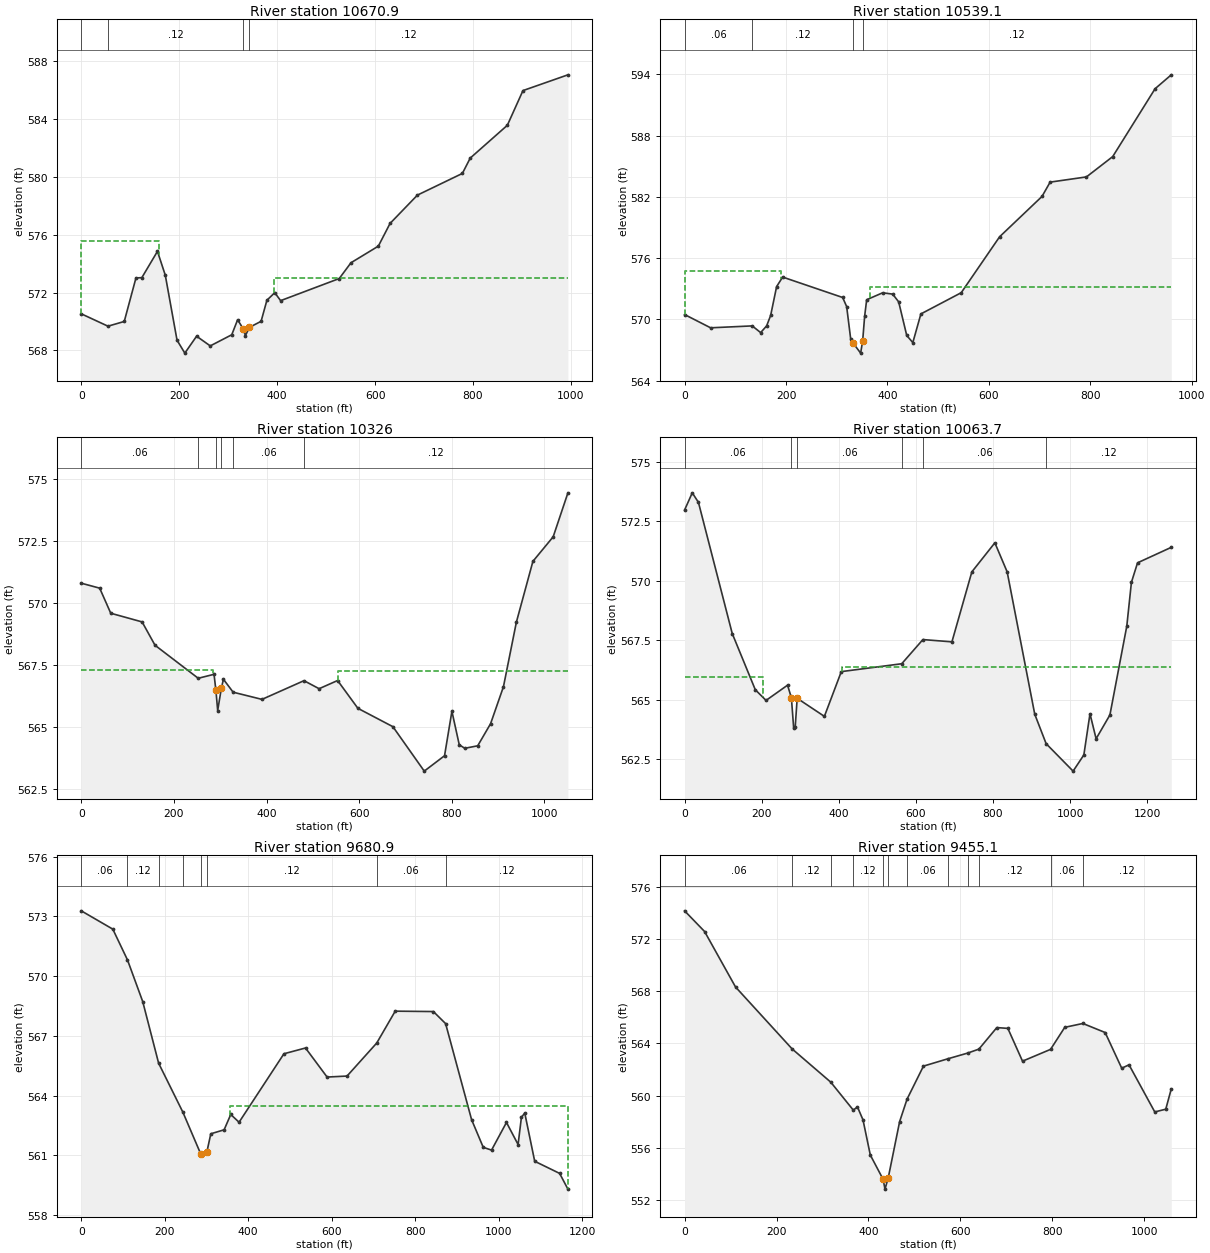
Type RM Length L Ch R = 1 ,10670.9 ,113.5,131.7,149.5
XS GIS Cut Line= 2
     2375828.551      301469.938     2375514.315       300527.23
#Sta/Elev= 30
       0  570.53   54.57569.6733    87.8     570   111.7  573.01   123.7  573.03
   155.6  574.85   171.6   573.2   195.6   568.7   211.5  567.81   235.5  568.98
   263.4  568.31   307.3  569.08   319.3  570.12   331.2  569.46   335.2  569.02
   343.2  569.59   367.2  570.01   379.1  571.47   395.1  571.99   407.1  571.44
   526.8  572.97   550.7  574.06   606.6  575.21   630.5  576.78   686.4  578.74
   778.2  580.24   794.2   581.3     870  583.57   901.9  585.97   993.7  587.06
#Mann= 4 ,-1 , 0
       0     .06       0   54.57     .12       0   331.2    .045       0
   343.2     .12       0
#XS Ineff= 2 , 0
          157.89   575.6  394.22          572.98
Permanent Ineff=
       F       F
Bank Sta=331.2,343.2
XS Rating Curve= 0 ,0
Exp/Cntr=0.3,0.1

Type RM Length L Ch R = 1 ,10539.1 ,212,213.2,214.5
XS GIS Cut Line= 4
      2375867.57      301442.204     2375789.445      301260.997
     2375881.676      301055.919     2375696.129      300551.362
#Sta/Elev= 30
       0  570.47    51.3  569.17  133.38569.3569     150   568.7   161.8  569.36
   169.7  570.38   181.5  573.21   193.4  574.14   311.7  572.14   319.6  571.25
   327.5   568.1   331.5  567.73   347.2  566.69   351.2   567.9   355.1  570.31
   359.1  571.92   390.6   572.6   410.4  572.47   422.2  571.71   438.1  568.42
   450.1  567.72     466  570.53   545.6  572.61   621.3  578.09   704.9  582.04
   720.9  583.44   792.5  583.95   844.3  585.94   927.9  592.59   959.8  593.95
#Mann= 4 ,-1 , 0
       0     .06       0  133.38     .12       0   331.5    .045       0
   351.2     .12       0
#XS Ineff= 2 , 0
          190.92  574.73  366.36          573.16
Permanent Ineff=
       F       F
Bank Sta=331.5,351.2
XS Rating Curve= 0 ,0
Exp/Cntr=0.3,0.1

Type RM Length L Ch R = 1 ,10326   ,259.4,262.2,265.1
XS GIS Cut Line= 3
     2375880.591       301464.99     2376273.386      300799.843
     2376181.155      300537.256
#Sta/Elev= 30
       0  570.81    39.8  570.61    63.7   569.6   131.4  569.25   159.3  568.31
  252.59  566.98   286.7  567.14   290.7   566.5   294.6  565.68   302.6  566.59
     307  566.94  327.94566.4192   390.2  566.13   480.9566.8832   513.6  566.56
   553.5  566.89   597.3  565.77   672.9  565.03   740.6  563.24   784.4  563.86
   800.3  565.65   816.2   564.3   828.1  564.16     856  564.26   883.8  565.15
   911.6  566.64   939.5  569.24   975.2  571.69    1019  572.68  1050.8  574.45
#Mann= 6 ,-1 , 0
       0     .06       0  252.59     .12       0   290.7    .045       0
   302.6     .12       0  327.94     .06       0   480.9     .12       0
#XS Ineff= 2 , 0
          283.59  567.32   554.8          567.27
Permanent Ineff=
       F       F
Bank Sta=290.7,302.6
XS Rating Curve= 0 ,0
Exp/Cntr=0.3,0.1

Type RM Length L Ch R = 1 ,10063.7 ,400.6,382.8,361
XS GIS Cut Line= 3
     2376045.521      301591.943     2376484.974      301045.068
     2376320.423       300508.56
#Sta/Elev= 30
       0  572.98    19.9   573.7    35.9   573.3   123.6  567.79   183.4  565.43
   211.3  564.98   267.1  565.62   277.1  565.09     283  563.82     287  563.86
   292.1  565.07   362.7  564.31   406.6  566.19  563.38566.5207  618.31567.5361
   693.6  567.44   745.3  570.38     805   571.6   836.9  570.38   908.5   564.4
  937.99563.1641    1008  562.01  1035.9  562.69  1051.8  564.42  1067.7  563.37
  1103.5  564.37  1147.3   568.1  1159.3  569.94  1175.2  570.76  1262.7  571.41
#Mann= 6 ,-1 , 0
       0     .06       0   277.1    .045       0   292.1     .06       0
  563.38     .12       0  618.31     .06       0  937.99     .12       0
#XS Ineff= 2 , 0
          202.27  565.97  407.43          566.38
Permanent Ineff=
       F       F
Bank Sta=277.1,292.1
XS Rating Curve= 0 ,0
Exp/Cntr=0.3,0.1

Type RM Length L Ch R = 1 ,9680.9  ,236.1,225.9,215.7
XS GIS Cut Line= 3
     2376581.849      301730.528     2376538.881      301214.903
     2376617.298       300571.06
#Sta/Elev= 30
       0  573.28    75.6  572.36  110.75 570.815   147.3  568.72  185.38 565.626
  243.61563.1595   286.2  561.07   301.2  561.19   310.4  562.08   342.3  562.28
   358.2  563.05   378.1  562.66   485.6   566.1   537.3  566.39     589  564.93
   636.8  564.98  707.95566.6397   752.2  568.24   843.7  568.22  872.95567.6142
   935.2  562.79   963.1   561.4     983  561.26  1018.8  562.65  1046.6  561.54
  1054.6  562.91  1062.6  563.12  1086.4   560.7  1146.1  560.09    1166   559.3
#Mann= 8 ,-1 , 0
       0     .06       0  110.75     .12       0  185.38     .06       0
  243.61     .12       0   286.2    .045       0   301.2     .12       0
  707.95     .06       0  872.95     .12       0
#XS Ineff= 2 , 0
                          356.66          563.46
Permanent Ineff=
       F       F
Bank Sta=286.2,301.2
XS Rating Curve= 0 ,0
Exp/Cntr=0.3,0.1

Type RM Length L Ch R = 1 ,9455.1  ,362.8,369,373.8
XS GIS Cut Line= 4
      2376650.86      301717.507     2376769.349       301381.57
     2376663.881       301194.07     2376702.368      300708.213
#Sta/Elev= 30
       0  574.19    43.5   572.6   110.8  568.34  233.91563.5811  317.97561.0286
   366.9558.8835   376.1  559.12   388.1  558.13     404  555.43   431.9  553.56
   435.9  552.81   442.9  553.66   467.8     558  483.98559.7264   519.6  562.26
  573.38  562.83  615.54563.2588  640.18563.5654   679.2  565.22   703.2  565.16
   735.1  562.64  796.13563.5469     827  565.24   866.4 565.536   914.9  564.84
   950.9   562.1   966.8  562.36  1022.8  558.74  1046.7  558.95  1058.7  560.51
#Mann= 12 ,-1 , 0
       0     .06       0  233.91     .12       0  317.97     .06       0
   366.9     .12       0   431.9    .045       0   442.9     .12       0
  483.98     .06       0  573.38     .12       0  615.54     .06       0
  640.18     .12       0  796.13     .06       0   866.4     .12       0
Bank Sta=431.9,442.9
XS Rating Curve= 0 ,0
Exp/Cntr=0.3,0.1

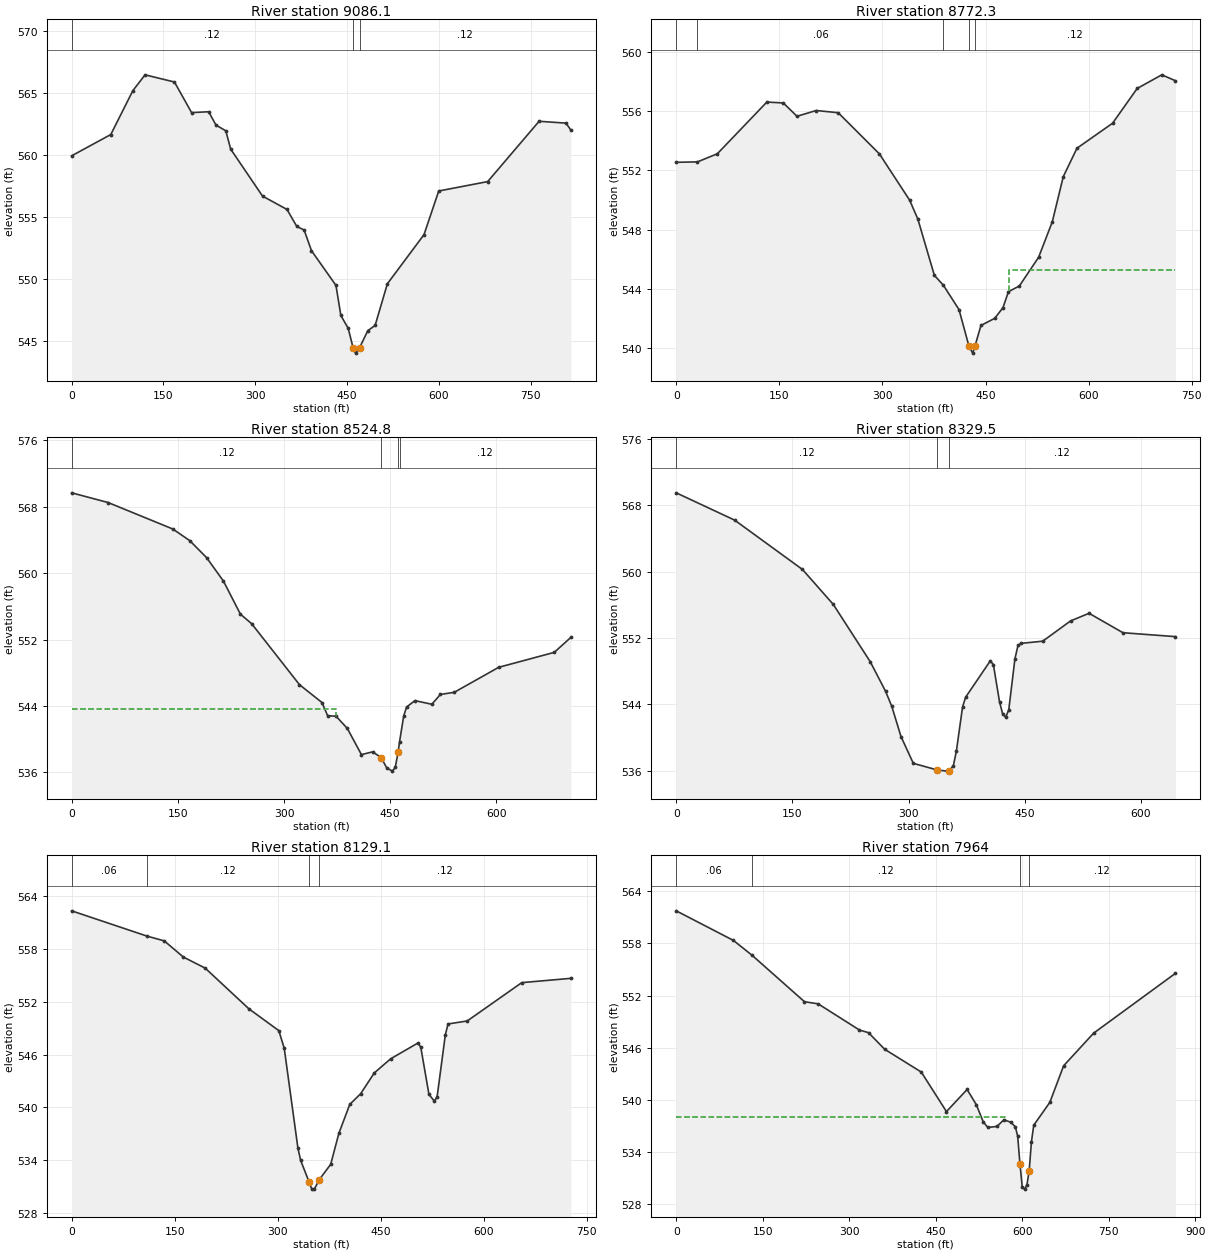
Type RM Length L Ch R = 1 ,9086.1  ,313.6,313.7,313.9
XS GIS Cut Line= 2
     2377184.714      301602.924     2376954.245      300820.372
#Sta/Elev= 30
       0  559.96      64  561.68     100  565.22     120   566.5     168  565.92
     196  563.45   223.9  563.52   235.9  562.44   251.9  561.98   259.9   560.5
   311.9  556.71   351.9  555.63   367.9  554.26   379.9  553.97   391.9   552.3
   431.9   549.5   439.9  547.07   451.9  546.03   459.9  544.46   463.9  544.03
   470.5  544.47   483.9  545.84   495.9  546.27   515.9  549.63   575.8   553.6
   599.8  557.12   679.8  557.88   763.8  562.75   807.8   562.6   815.8  562.03
#Mann= 3 ,-1 , 0
       0     .12       0   459.9    .045       0   470.5     .12       0
Bank Sta=459.9,470.5
XS Rating Curve= 0 ,0
Exp/Cntr=0.3,0.1

Type RM Length L Ch R = 1 ,8772.3  ,237.8,247.6,257.2
XS GIS Cut Line= 3
     2377476.381      301498.757     2377330.547      300992.247
     2377167.787      300877.664
#Sta/Elev= 30
       0  552.55   30.96  552.58    59.9  553.13   131.8  556.62   155.7  556.56
   175.7  555.66   203.6  556.05   235.6   555.9   295.5  553.12   339.4     550
   351.4  548.72   375.4  544.92  388.49544.2484   411.3   542.6   425.7 540.134
   431.2  539.66   434.3  540.11   443.2  541.53   463.2  542.01   475.2  542.73
   483.2  543.81   499.1   544.2   527.1  546.14     547  548.54   562.9  551.58
   582.8   553.5   634.6  555.19   670.4  557.54   706.2  558.46   726.1  558.06
#Mann= 5 ,-1 , 0
       0     .12       0   30.96     .06       0  388.49     .12       0
   425.7    .045       0   434.3     .12       0
#XS Ineff= 2 , 0
                           483.8           545.3
Permanent Ineff=
       F       F
Bank Sta=425.7,434.3
XS Rating Curve= 0 ,0
Exp/Cntr=0.3,0.1

Type RM Length L Ch R = 1 ,8524.8  ,202,195.3,188.5
XS GIS Cut Line= 4
     2377801.902      301409.565     2377579.245      301155.659
     2377606.589      300974.669     2377536.277      300804.096
#Sta/Elev= 30
       0  569.67    51.6   568.5     143  565.31   166.9  563.91   190.7  561.86
   214.5  559.03   238.4  555.06   254.3  553.91   321.8  546.57   353.6  544.42
   361.6  542.83   373.5  542.77   389.4   541.3   409.3  538.15   425.2  538.48
   437.2  537.79   445.1  536.54   453.1  536.16   457.1  536.62   461.1  538.42
   463.2  539.72     469  542.78     473  543.87   484.9  544.65   508.8  544.21
   520.8  545.39   540.4  545.65   603.2  548.66   681.7  550.46   705.2  552.27
#Mann= 4 ,-1 , 0
       0     .12       0   437.2    .045       0   461.1    .045       0
   463.2     .12       0
#XS Ineff= 2 , 0
          373.99  543.69
Permanent Ineff=
       F       F
Bank Sta=437.2,461.1
XS Rating Curve= 0 ,0
Exp/Cntr=0.3,0.1

Type RM Length L Ch R = 1 ,8329.5  ,221.1,200.5,179.9
XS GIS Cut Line= 3
     2377830.547      301347.716     2377762.839      300907.612
     2377596.172      300798.237
#Sta/Elev= 30
       0  569.49    75.5   566.2     163  560.26   202.8  556.05   250.5  549.15
   270.4  545.57   278.3  543.78   290.2  540.14   306.1  536.91   337.3   536.1
   349.9  535.97   352.3  536.03   357.8   536.6   361.8  538.43   369.7   543.7
   373.7  544.88   405.5  549.25   409.5   548.8   417.4  544.34   421.4  542.88
   425.4  542.45   429.4  543.38   437.3  549.49   441.3  551.12   445.3  551.36
   473.2  551.62   509.1  554.06     533  554.98   576.8  552.64   644.6  552.17
#Mann= 3 ,-1 , 0
       0     .12       0   337.3    .045       0   352.3     .12       0
Bank Sta=337.3,352.3
XS Rating Curve= 0 ,0
Exp/Cntr=0.3,0.1

Type RM Length L Ch R = 1 ,8129.1  ,183.1,165.1,147
XS GIS Cut Line= 3
     2378062.318      301300.841     2378055.808      301046.935
     2377653.464      300798.237
#Sta/Elev= 30
       0  562.36  109.38559.4929   134.9  558.94   162.7   557.1   194.5  555.84
     258  551.22   301.7  548.73   309.6  546.71   329.5  535.36   333.5  533.96
   345.6  531.55   349.4  530.76   353.4   530.7   360.6  531.78   377.2  533.52
   389.1  537.04     405  540.34   420.9  541.56   440.8  543.93   464.6  545.53
   504.4  547.33   508.4  546.84   520.3  541.47   528.2  540.71   532.2  541.22
   544.2  548.28   548.1  549.49     576  549.83   655.4  554.19     727  554.68
#Mann= 4 ,-1 , 0
       0     .06       0  109.38     .12       0   345.6    .045       0
   360.6     .12       0
Bank Sta=345.6,360.6
XS Rating Curve= 0 ,0
Exp/Cntr=0.3,0.1

Type RM Length L Ch R = 1 ,7964    ,253,294.1,334
XS GIS Cut Line= 4
     2378106.589      301276.101     2378072.735      300808.653
     2377808.412      300868.549     2377700.339      300803.445
#Sta/Elev= 30
       0  561.76    99.3  558.35   131.6 556.642   222.4   551.3   246.2  551.05
   317.7  548.04   333.6  547.73   361.4  545.83     425   543.2   468.7  538.65
   504.5  541.19   520.5  539.44   532.4  537.48   540.4  536.82   556.4  536.94
   568.3  537.71   580.3  537.42   588.2  536.89   592.2  535.82   596.2   532.6
   600.2  529.93   604.2  529.72   608.2  530.18   612.2  531.86   616.1  535.18
   620.1  537.08     648  539.71   671.9  543.92   723.8  547.67   865.9  554.57
#Mann= 4 ,-1 , 0
       0     .06       0   131.6     .12       0   596.2    .045       0
   612.2     .12       0
#XS Ineff= 2 , 0
          570.69  538.04
Permanent Ineff=
       F       F
Bank Sta=596.2,612.2
XS Rating Curve= 0 ,0
Exp/Cntr=0.3,0.1

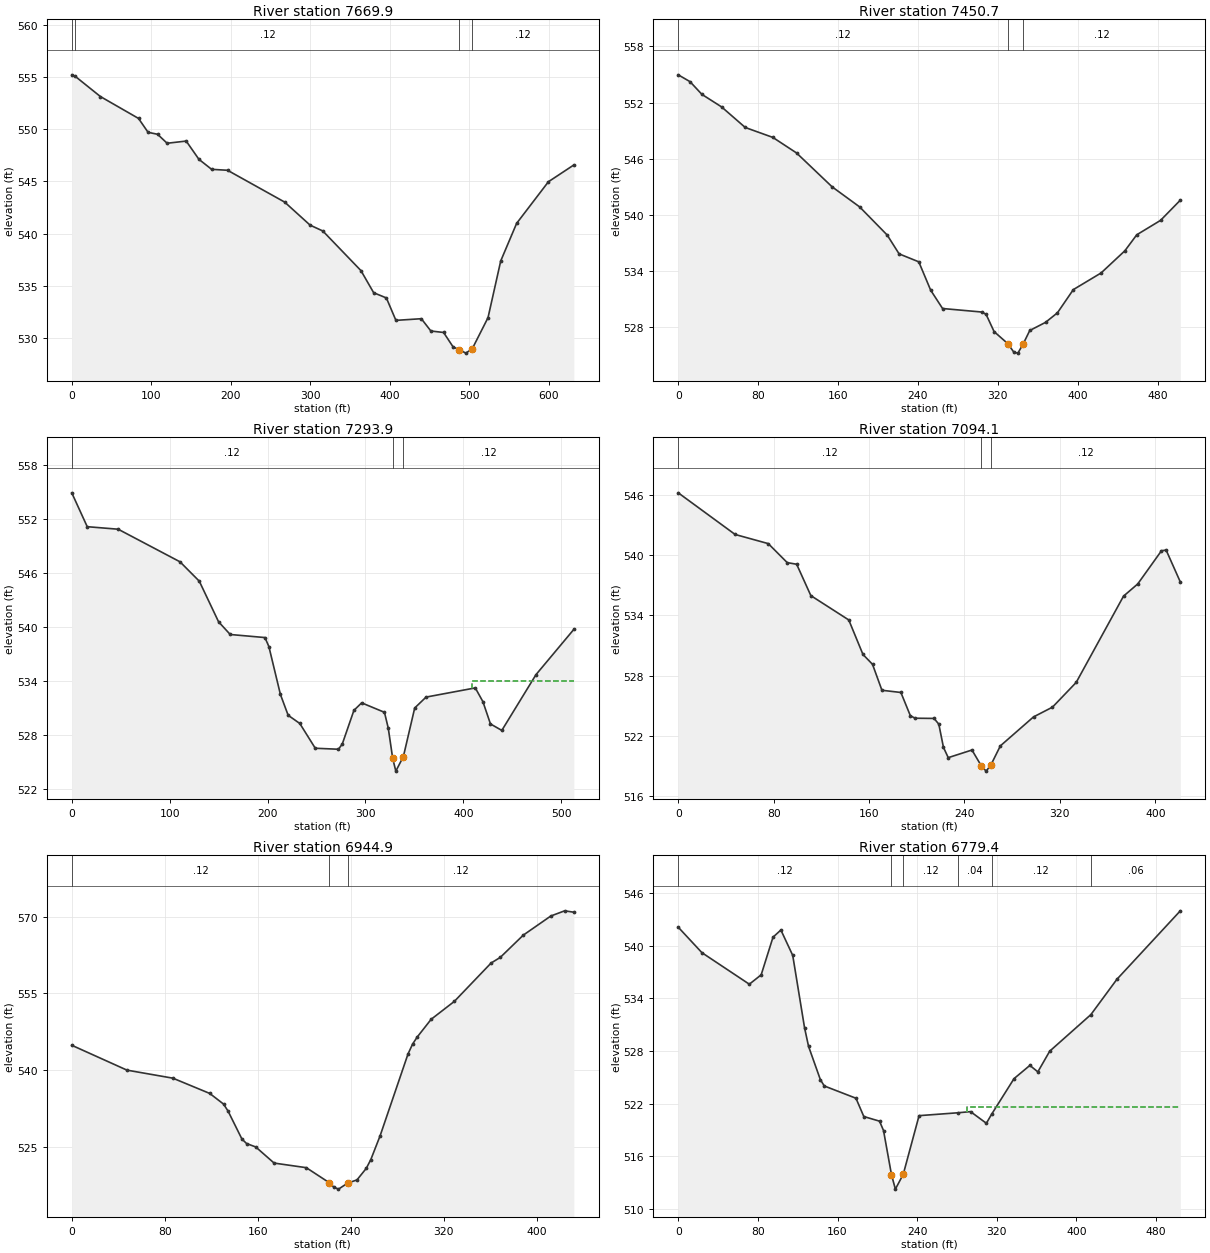
Type RM Length L Ch R = 1 ,7669.9  ,218.9,219.2,219
XS GIS Cut Line= 2
     2378160.235      301148.844     2378115.096      300518.636
#Sta/Elev= 30
       0  555.22     4.6555.0605      36  553.14      84  551.04      96  549.71
     108  549.52     120  548.66     144  548.87     160  547.12     176  546.16
     196  546.07   267.9  543.02   299.9  540.81   315.9  540.25   363.9  536.45
   379.9  534.33   395.9  533.83   407.9  531.68   439.9  531.84   451.9  530.66
   467.9  530.52   479.9  529.13   487.9  528.86   495.9  528.54   503.9  528.95
   523.8  531.94   539.8  537.38   559.8  540.98   599.8  544.97   631.8  546.58
#Mann= 4 ,-1 , 0
       0     .06       0     4.6     .12       0   487.9    .045       0
   503.9     .12       0
Bank Sta=487.9,503.9
XS Rating Curve= 0 ,0
Exp/Cntr=0.3,0.1

Type RM Length L Ch R = 1 ,7450.7  ,134.5,156.8,178.9
XS GIS Cut Line= 3
     2378422.388      300989.122     2378344.263      300753.011
     2378328.638      300499.539
#Sta/Elev= 30
       0  554.96    11.8  554.23    23.7  552.87    43.4  551.53    67.1  549.33
    94.7  548.27   118.4  546.61     154  542.99   181.6  540.84   209.2  537.83
   221.1  535.82   240.8  534.97   252.7  531.94   264.6  529.98   304.2   529.6
   308.2  529.35   316.2  527.51  330.06526.2086     336   525.3     340  525.21
  345.19 526.166   351.9  527.63   367.7   528.5   379.6  529.52   395.5     532
   423.3  533.78   447.1  536.15     459  537.86   482.8   539.4   502.6  541.56
#Mann= 3 ,-1 , 0
       0     .12       0  330.06    .045       0  345.19     .12       0
Bank Sta=330.06,345.19
XS Rating Curve= 0 ,0
Exp/Cntr=0.3,0.1

Type RM Length L Ch R = 1 ,7293.9  ,219.5,199.8,178.7
XS GIS Cut Line= 4
     2378521.346      300959.608     2378464.054      300660.997
     2378545.652      300595.893     2378536.971      300491.726
#Sta/Elev= 30
       0  554.89    15.8  551.13    47.4  550.85   110.6  547.23   130.3  545.08
     150  540.57   161.9  539.16   197.4  538.82   201.4  537.82   213.2   532.5
   221.1  530.19     233  529.28   248.8  526.53   272.5  526.42   276.4     527
   288.3  530.74   296.2  531.57   319.5  530.52   323.4  528.75   327.9  525.41
   331.1  523.99   338.8   525.6   350.4     531     362  532.21   412.3  533.23
   420.1   531.7   427.8  529.23   439.4  528.51   474.3   534.7     513  539.73
#Mann= 3 ,-1 , 0
       0     .12       0   327.9    .045       0   338.8     .12       0
#XS Ineff= 2 , 0
                          408.67          534.01
Permanent Ineff=
       F       F
Bank Sta=327.9,338.8
XS Rating Curve= 0 ,0
Exp/Cntr=0.3,0.1

Type RM Length L Ch R = 1 ,7094.1  ,147.9,149.2,150.3
XS GIS Cut Line= 2
     2378665.443      300891.032     2378659.367      300470.025
#Sta/Elev= 30
       0  546.18    47.7  542.04    75.5  541.13    91.4  539.24    99.3  539.08
   111.2  535.96     143  533.54   154.9  530.11   162.9  529.13   170.8  526.55
   186.7  526.33   194.6  524.03   198.6  523.77   214.5  523.75   218.5  523.18
   222.4  520.87   226.4  519.85   246.3  520.61   254.2  519.02   258.2  518.51
   262.2  519.13   270.1  521.02   297.9   523.9   313.8  524.87   333.7  527.33
   373.4  535.91   385.3  537.12   405.2  540.42   409.1  540.49     421  537.32
#Mann= 3 ,-1 , 0
       0     .12       0   254.2    .045       0   262.2     .12       0
Bank Sta=254.2,262.2
XS Rating Curve= 0 ,0
Exp/Cntr=0.3,0.1

Type RM Length L Ch R = 1 ,6944.9  ,155.1,165.4,175.5
XS GIS Cut Line= 4
       2378805.2      300867.594     2378810.409      300626.275
     2378814.749      300538.601     2378730.547      300479.573
#Sta/Elev= 30
       0  544.87    47.5  540.01      87  538.44   118.7  535.46   130.6  533.38
   134.5     532   146.4  526.55   150.4  525.67   158.3     525   174.1  521.85
   201.8  520.95   221.6  518.01   225.6  517.13   229.5  516.76   237.4  517.94
   245.4  518.56   253.4  520.82   257.3  522.53   265.3  527.18   289.3  543.16
   293.2  545.08   297.2  546.47   309.2  549.94   329.2  553.45   360.8  560.94
   368.7  562.04   388.5  566.39   412.2  570.13   424.1  571.14     432  570.87
#Mann= 3 ,-1 , 0
       0     .12       0   221.6    .045       0   237.4     .12       0
Bank Sta=221.6,237.4
XS Rating Curve= 0 ,0
Exp/Cntr=0.3,0.1

Type RM Length L Ch R = 1 ,6779.4  ,155.7,143.3,130.7
XS GIS Cut Line= 3
     2378869.313       300871.79      2378978.41      300651.442
     2378799.869      300464.672
#Sta/Elev= 30
       0  542.14    23.8  539.23    71.4  535.63    83.3   536.7    95.2     541
   103.1  541.82     115  538.92   126.9  530.64   130.9  528.53   142.8  524.72
   146.7  524.01   178.5  522.61   186.4  520.52   202.2  519.99   206.2  518.92
   214.2  513.87   218.1  512.23     226  513.92   241.9  520.62  281.15520.9508
   293.6  521.08   309.5  519.75  314.71520.7703   337.3  524.85   353.2  526.36
   361.2  525.62   373.1  527.98   414.5532.1625   440.6  536.19   504.3  544.01
#Mann= 6 ,-1 , 0
       0     .12       0   214.2    .045       0     226     .12       0
  281.15     .04       0  314.71     .12       0   414.5     .06       0
#XS Ineff= 2 , 0
                           290.4          521.65
Permanent Ineff=
       F       F
Bank Sta=214.2,226
XS Rating Curve= 0 ,0
Exp/Cntr=0.3,0.1

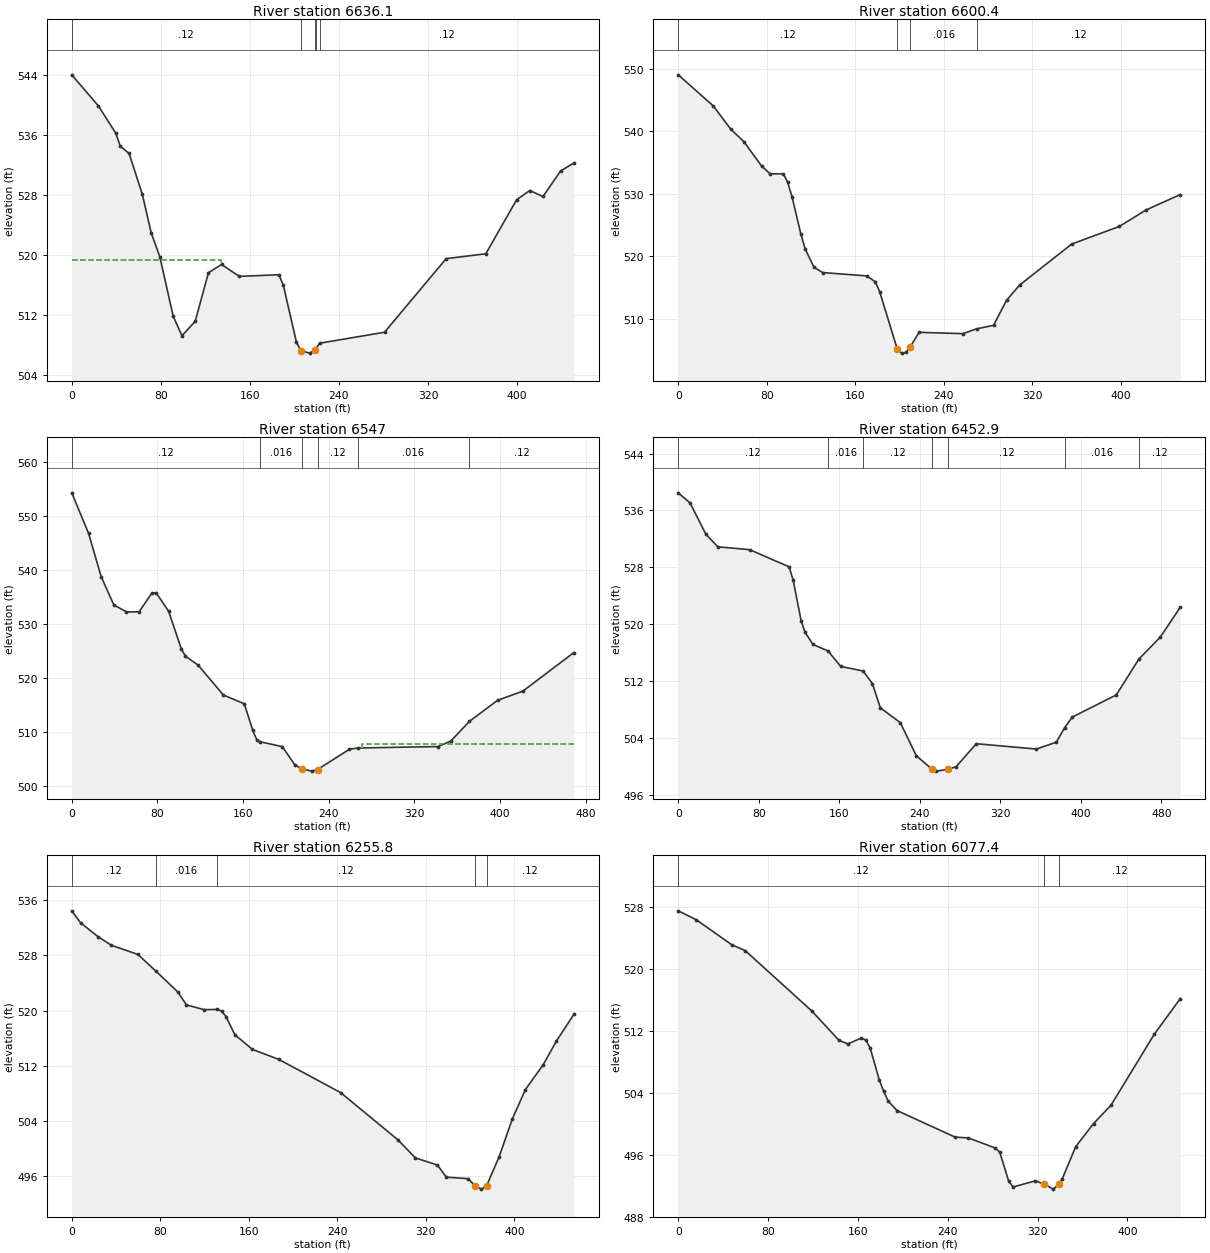
Type RM Length L Ch R = 1 ,6636.1  ,41,35.8,30.6
XS GIS Cut Line= 3
     2379173.654      300883.943      2379112.89      300716.408
     2379087.716      300444.707
#Sta/Elev= 30
       0  544.03    23.8   539.9    39.6  536.22    43.6  534.49    51.5  533.53
    63.4  528.07    71.3  522.96    79.2  519.68    91.1   511.8      99  509.18
   110.9   511.1   122.8   517.6   134.6   518.7   150.5  517.11   186.1  517.33
   190.1  515.91   201.9   508.3   205.9  507.18   213.8  506.86   218.8   507.3
  219.13507.3796  222.63508.1814     281  509.65   336.4  519.48     372  520.13
   399.7  527.35   411.5  528.58   423.4  527.78   439.2  531.19   451.1  532.25
#Mann= 5 ,-1 , 0
       0     .12       0   205.9    .045       0   218.8     .12       0
  219.13    .016       0  222.63     .12       0
#XS Ineff= 2 , 0
          134.16  519.32
Permanent Ineff=
       F       F
Bank Sta=205.9,218.8
XS Rating Curve= 0 ,0
Exp/Cntr=0.3,0.1

Type RM Length L Ch R = 1 ,6600.4  ,62.4,53.4,44
XS GIS Cut Line= 3
     2379207.508       300876.13     2379122.438      300612.241
     2379108.549      300436.026
#Sta/Elev= 30
       0  549.05    31.7  544.07    47.5  540.34    59.4  538.34    75.3  534.46
    83.2  533.18    95.1  533.21      99  531.82     103  529.45   110.9  523.53
   114.9   521.1   122.8  518.22   130.7  517.38   170.3  516.85   178.2  515.92
   182.2   514.3     198  505.15     202  504.48     206  504.59   209.9  505.52
   217.8  507.81   257.5   507.6  269.87508.3701   285.1  508.93   296.9  512.95
   308.7  515.38   355.8  521.95     399  524.78   422.6  527.37     454  529.88
#Mann= 4 ,-1 , 0
       0     .12       0     198    .045       0   209.9    .016       0
  269.87     .12       0
Bank Sta=198,209.9
XS Rating Curve= 0 ,0
Exp/Cntr=0.3,0.1

Type RM Length L Ch R = 1 ,6547    ,98.4,94.1,89.2
XS GIS Cut Line= 4
     2379247.438      300868.318      2379210.98      300679.082
     2379154.556      300613.977     2379153.688      300423.873
#Sta/Elev= 30
       0  554.34    15.7  546.81    27.5  538.78    39.3  533.54    51.1  532.26
    62.9  532.26    74.7  535.71    78.7  535.83    90.5  532.36   102.3   525.4
   106.2  524.04     118  522.38   141.6  516.84   161.2   515.2   169.1  510.26
     173  508.45  175.45508.1805   196.6  507.27   208.4  503.88   214.6503.1589
     224  502.72   229.6503.0212   259.3  506.77  267.01507.0077   342.2  507.28
   354.1   508.3  371.42511.9441   397.7  515.85   421.4  517.56     469  524.71
#Mann= 6 ,-1 , 0
       0     .12       0  175.45    .016       0   214.6    .045       0
   229.6     .12       0  267.01    .016       0  371.42     .12       0
#XS Ineff= 2 , 0
                           270.9           507.7
Permanent Ineff=
       F       F
Bank Sta=214.6,229.6
XS Rating Curve= 0 ,0
Exp/Cntr=0.3,0.1

Type RM Length L Ch R = 1 ,6452.9  ,184.5,197.1,208.4
XS GIS Cut Line= 4
     2379305.598      300863.977     2379317.751      300655.644
      2379179.73      300529.776     2379178.862      300426.477
#Sta/Elev= 30
       0  538.48    11.8  537.04    27.6  532.62    39.4  530.88    70.9  530.48
   110.2  528.06   114.2  526.16   122.1  520.47     126  518.84   133.9  517.13
  148.82  516.22   161.4  514.04  183.67513.3965   192.9  511.62   200.8  508.21
   220.6  506.13   236.5  501.47   252.4  499.53   256.4   499.3   268.3  499.55
   276.2  499.94   296.1  503.16   355.7  502.41   375.6  503.37  383.78505.4003
   391.5  506.91   435.2  510.03  457.66515.0789   478.9  518.16   498.8  522.38
#Mann= 7 ,-1 , 0
       0     .12       0  148.82    .016       0  183.67     .12       0
   252.4    .045       0   268.3     .12       0  383.78    .016       0
  457.66     .12       0
Bank Sta=252.4,268.3
XS Rating Curve= 0 ,0
Exp/Cntr=0.3,0.1

Type RM Length L Ch R = 1 ,6255.8  ,169.9,178.4,185.7
XS GIS Cut Line= 3
     2379364.626        300836.2     2379383.723      300534.116
     2379341.188      300389.151
#Sta/Elev= 30
       0  534.46       8  532.72    23.9   530.7    35.8  529.47    59.7  528.15
   76.04525.7281    95.6  522.75   103.6  520.84   119.5  520.15   131.2 520.177
   135.4  519.95   139.4  519.14   147.4  516.52   163.3  514.39   187.2  512.94
     243  508.14   294.7  501.31   310.6  498.68   330.5  497.65   338.5   495.9
   358.4  495.67   364.5  494.63   370.3  494.16  375.05494.6799   386.2  498.81
   398.1  504.28     410  508.58   425.9  512.12   437.9  515.56   453.8  519.47
#Mann= 5 ,-1 , 0
       0     .12       0   76.04    .016       0   131.2     .12       0
   364.5    .045       0  375.05     .12       0
Bank Sta=364.5,375.05
XS Rating Curve= 0 ,0
Exp/Cntr=0.3,0.1

Type RM Length L Ch R = 1 ,6077.4  ,213.9,230.9,246.6
XS GIS Cut Line= 3
     2379518.272      300771.963     2379539.105        300398.7
     2379513.063      300330.123
#Sta/Elev= 30
       0  527.56    15.9  526.42    47.7  523.17    59.7  522.41   119.3  514.56
   143.2   510.8   151.1  510.35   163.1   511.1     167  510.86     171   509.8
     179  505.72     183   504.2   186.9  502.98   194.9  501.72   246.6  498.29
   258.5  498.18   282.4  496.88   286.4  496.33   294.3  492.61   298.3  491.84
   318.2  492.64   326.1  492.19   334.1  491.56  339.04492.1827     342  492.87
     354  497.05   369.9  500.04   385.4   502.4     424  511.59   447.2  516.21
#Mann= 3 ,-1 , 0
       0     .12       0   326.1    .045       0  339.04     .12       0
Bank Sta=326.1,339.04
XS Rating Curve= 0 ,0
Exp/Cntr=0.3,0.1