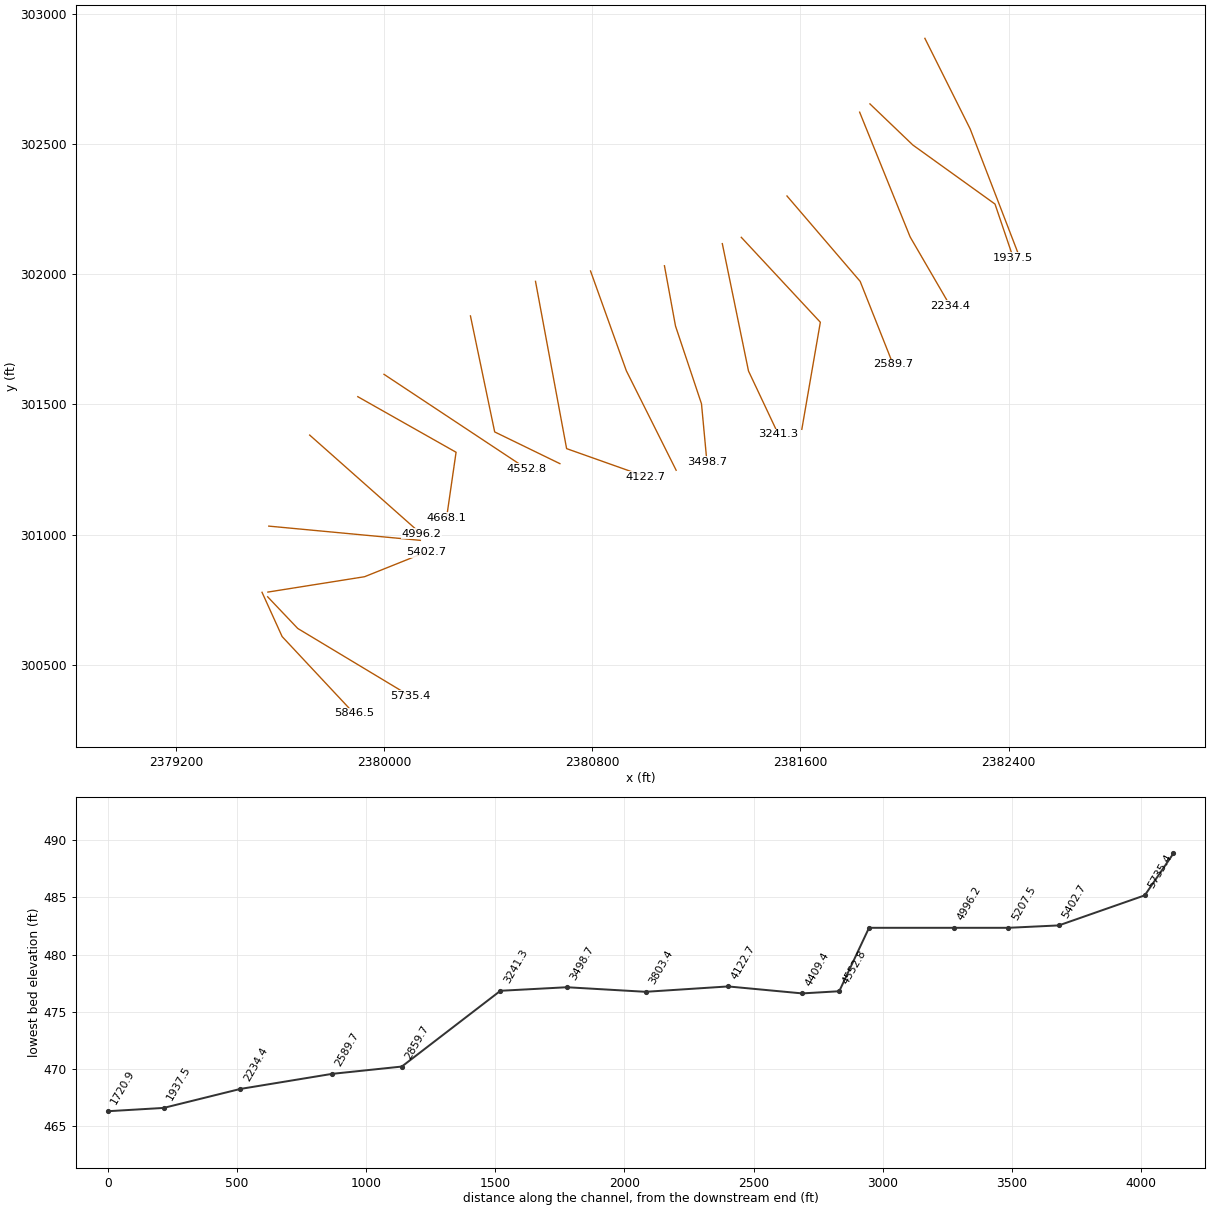
HEC-RAS study SYLVANRUN.prj: SYLVANRUN

--- SYLVANRUN.g01 (geometry) --- (continued)

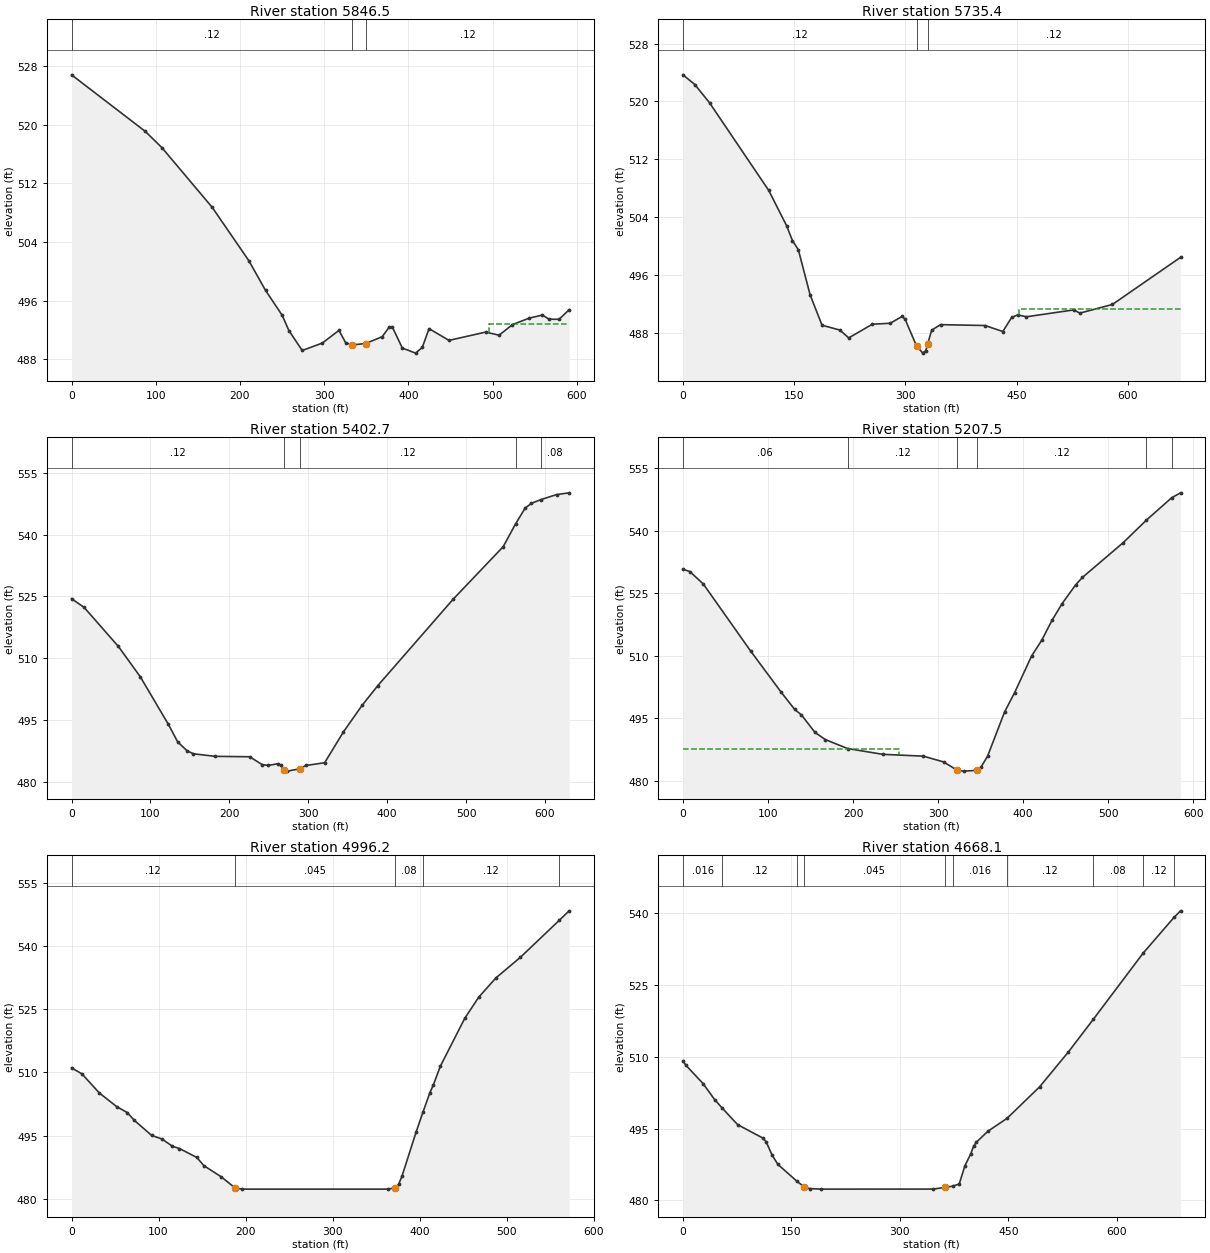
Type RM Length L Ch R = 1 ,5846.5  ,104.4,111.1,118
XS GIS Cut Line= 3
     2379531.292       300778.04     2379608.549      300607.901
     2379884.591      300312.762
#Sta/Elev= 30
       0  526.82    87.5  519.11   107.3  516.89     167  508.75   210.6  501.46
   230.4  497.41   250.2  494.01   258.2  491.92     274  489.21   297.8  490.22
   317.6  491.95   325.5  490.29   333.4  489.97   349.3  490.16   369.1   491.1
     377  492.36     381  492.42   392.9  489.54   408.7  488.85   416.6  489.63
   424.6  492.19   448.3  490.59   491.9  491.72   507.8   491.3   523.6  492.73
   543.4  493.62   559.3  494.05   567.2  493.47   579.1  493.47     591  494.77
#Mann= 3 ,-1 , 0
       0     .12       0   333.4    .045       0   349.3     .12       0
#XS Ineff= 2 , 0
                          495.98          492.84
Permanent Ineff=
       F       F
Bank Sta=333.4,349.3
XS Rating Curve= 0 ,0
Exp/Cntr=0.3,0.1

Type RM Length L Ch R = 1 ,5735.4  ,316.5,332.6,348.3
XS GIS Cut Line= 3
     2379552.994      300760.679     2379668.445      300639.151
     2380099.869      300379.602
#Sta/Elev= 30
       0  523.67      16  522.33    35.9   519.8   115.7  507.68   139.7  502.82
   147.7  500.74   155.6  499.49   171.6  493.21   187.6  489.04   211.6  488.37
   223.6  487.29   255.5  489.18   279.5  489.31   295.5  490.25   299.5  489.89
   315.1  486.16   323.5  485.18   327.5  485.52   330.1  486.46   335.4  488.35
   347.4  489.12   407.4     489   431.4  488.17   443.3  490.11   451.3  490.47
   463.3  490.21   527.2  491.16   535.2  490.71   579.2  491.91   671.1  498.43
#Mann= 3 ,-1 , 0
       0     .12       0   315.1    .045       0   330.1     .12       0
#XS Ineff= 2 , 0
                          452.94          491.32
Permanent Ineff=
       F       F
Bank Sta=315.1,330.1
XS Rating Curve= 0 ,0
Exp/Cntr=0.3,0.1

Type RM Length L Ch R = 1 ,5402.7  ,200.5,195.2,188.7
XS GIS Cut Line= 3
     2379553.862      300778.908      2379925.39      300837.936
     2380161.501      300932.554
#Sta/Elev= 30
       0  524.42    15.8  522.34    59.4  512.82    87.1  505.47   122.8  493.88
   134.6  489.62   146.5  487.49   154.4  486.76   182.2  486.14   225.7  486.04
   241.6  484.13   249.5  483.93   261.4  484.35   265.3  484.02   269.3  482.87
   273.2  482.55   289.1   483.1     297  483.92   320.8  484.59   344.5  492.06
   368.3  498.54   388.1  503.31   483.5  524.27   547.1  537.07  562.87542.6393
   574.9  546.44   582.9  547.59  594.73548.4756   614.6   549.7   630.6  550.13
#Mann= 5 ,-1 , 0
       0     .12       0   269.3    .045       0   289.1     .12       0
  562.87     .06       0  594.73     .08       0
Bank Sta=269.3,289.1
XS Rating Curve= 0 ,0
Exp/Cntr=0.3,0.1

Type RM Length L Ch R = 1 ,5207.5  ,231,211.3,172.3
XS GIS Cut Line= 2
     2379557.334       301032.38     2380139.799      300977.693
#Sta/Elev= 30
       0  530.73       8  530.19    23.9  527.21    79.6  511.12   115.4  501.28
   131.3  497.15   139.3  495.82   155.2  491.63   167.2  489.92  193.56487.7556
   234.8  486.37   282.6  485.93   306.4  484.55   322.4  482.55   330.3  482.34
   346.2  482.53   350.2  483.22   358.2  485.95   378.1  496.51     390  501.18
   409.9  509.94   421.9  513.74   433.8  518.45   445.7  522.48   461.6  526.97
   469.6  528.77   517.4  537.07  544.95542.5219  574.55  547.87     585  549.05
#Mann= 6 ,-1 , 0
       0     .06       0  193.56     .12       0   322.4    .045       0
   346.2     .12       0  544.95     .06       0  574.55     .08       0
#XS Ineff= 2 , 0
          254.49  487.69
Permanent Ineff=
       F       F
Bank Sta=322.4,346.2
XS Rating Curve= 0 ,0
Exp/Cntr=0.3,0.1

Type RM Length L Ch R = 1 ,4996.2  ,317.7,328.1,356.7
XS GIS Cut Line= 2
     2379714.452      301382.207     2380142.404      301002.866
#Sta/Elev= 30
       0  511.11      12  509.66      32  505.13      52  501.89      64  500.51
      72  498.68      92  495.09     104  494.22     116   492.5     124  491.97
     144  489.85     152  487.92     172  485.27     188  482.61     196  482.34
   363.9  482.34   371.9  482.69   375.9  483.47   379.9  485.48   395.9  495.78
  403.84500.5738   411.9  505.22   415.9  507.08   423.9   511.5   451.9  522.83
   467.9  527.84   487.9  532.46   515.9  537.32  560.47546.0725   571.9  548.34
#Mann= 5 ,-1 , 0
       0     .12       0     188    .045       0   371.9     .08       0
  403.84     .12       0  560.47     .08       0
Bank Sta=188,371.9
XS Rating Curve= 0 ,0
Exp/Cntr=0.3,0.1

Type RM Length L Ch R = 1 ,4668.1  ,116.9,115.3,114.7
XS GIS Cut Line= 3
     2379899.348      301529.776     2380276.952      301316.234
     2380240.494      301064.498
#Sta/Elev= 30
       0   509.1       4  508.23    27.9  504.37    43.8  501.04   54.45499.2475
    75.6  495.81   111.4  492.93   115.4  492.11   123.4  489.42   131.3  487.51
  157.86 483.954   167.2  482.87   175.1  482.45     191  482.34   346.2  482.35
   362.2   482.7  372.95 482.957   382.1  483.41     390  487.23     398   489.7
     402  491.31   405.9  492.16   421.9  494.44  448.28497.1296   493.4  503.72
   533.2  511.01  567.53517.7955  636.19531.5726  679.16539.0832   688.2  540.46
#Mann= 10 ,-1 , 0
       0    .016       0   54.45     .12       0  157.86     .08       0
   167.2    .045       0   362.2     .12       0  372.95    .016       0
  448.28     .12       0  567.53     .08       0  636.19     .12       0
  679.16     .08       0
Bank Sta=167.2,362.2
XS Rating Curve= 0 ,0
Exp/Cntr=0.3,0.1

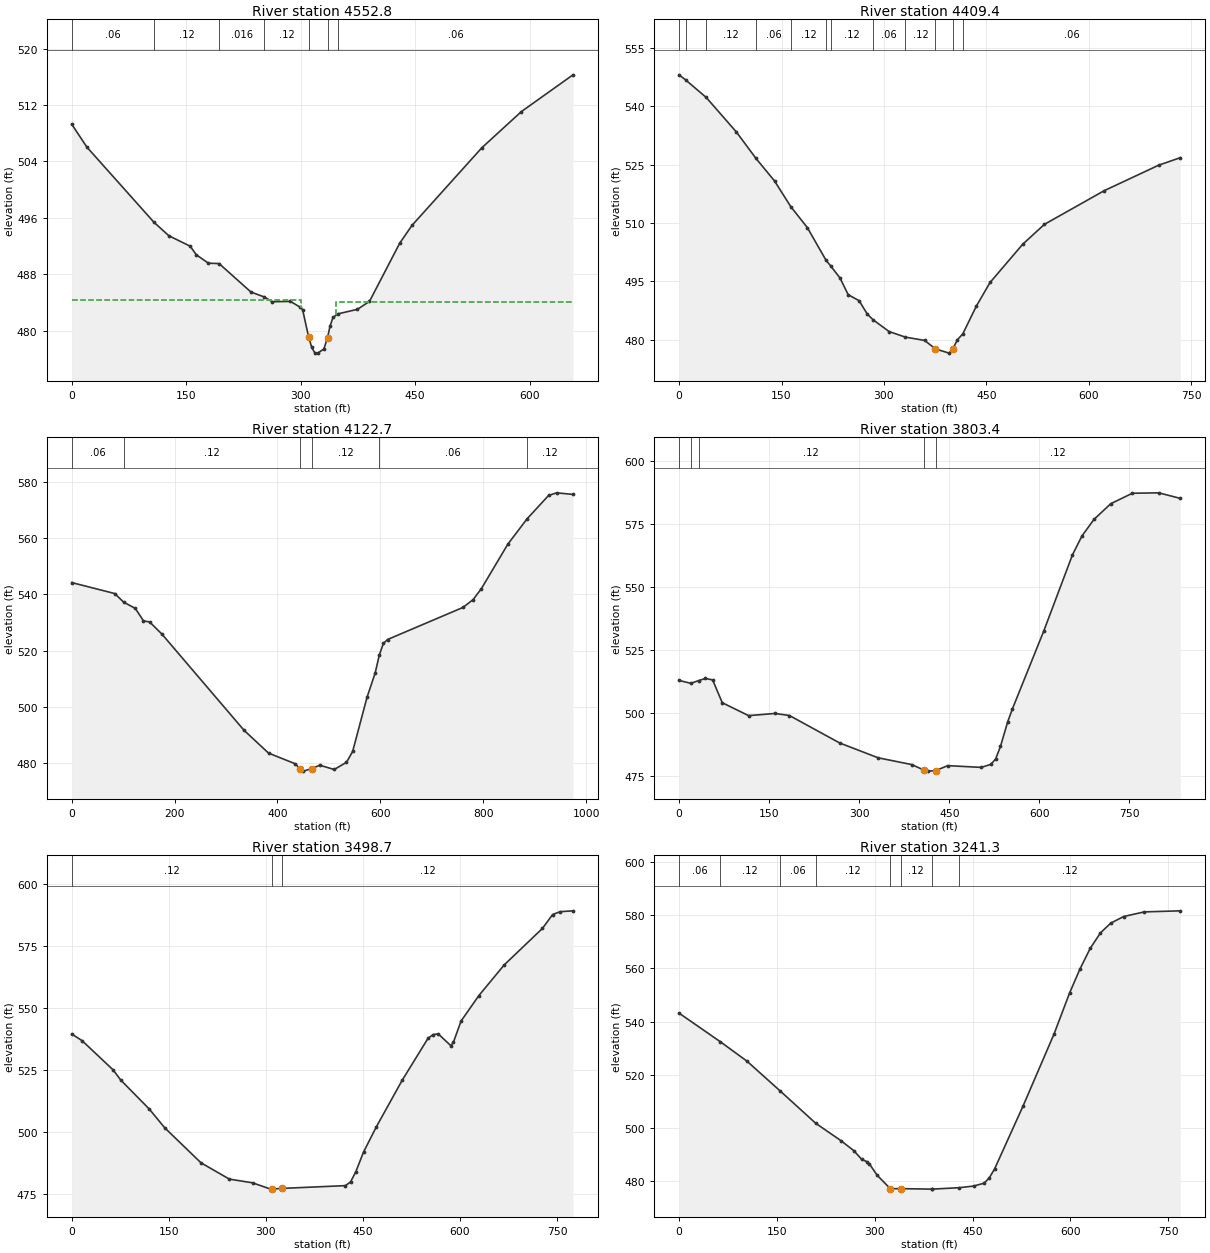
Type RM Length L Ch R = 1 ,4552.8  ,162.2,143.4,123.7
XS GIS Cut Line= 2
     2380000.042      301615.713     2380547.786      301252.866
#Sta/Elev= 30
       0  509.27    19.9  506.02  107.86495.3496   127.4  493.44   155.3  491.96
   163.3  490.74   179.2  489.55  193.13489.4985   234.9  485.46  252.31484.7599
   262.8  484.08   286.7  484.13   298.6  483.36   302.6  482.96   310.6  479.04
   314.6  477.59   318.6  476.82   322.5  476.79   330.5  477.38   335.3     479
   338.5  480.58   342.4  481.86  349.27 482.373   374.3     483   390.2  484.12
     430  492.41     446  494.92   537.6  505.94   589.3  511.06     657  516.28
#Mann= 7 ,-1 , 0
       0     .06       0  107.86     .12       0  193.13    .016       0
  252.31     .12       0   310.6    .045       0   335.3     .12       0
  349.27     .06       0
#XS Ineff= 2 , 0
          300.52  484.27  346.03           484.1
Permanent Ineff=
       F       F
Bank Sta=310.6,335.3
XS Rating Curve= 0 ,0
Exp/Cntr=0.3,0.1

Type RM Length L Ch R = 1 ,4409.4  ,286.4,286.8,285.9
XS GIS Cut Line= 3
     2380332.229      301840.157      2380425.39      301394.359
     2380675.979      301272.449
#Sta/Elev= 30
       0  548.07    9.46 546.781   39.72542.2641    83.9  533.39  112.68  526.59
   139.8  520.81  163.51514.2396   187.8  508.84  215.22500.4452   221.8499.0443
   235.7  495.88   247.7   491.6   263.7  490.06   275.6  486.63  284.07485.1754
   307.6  482.14  331.31480.7152   359.6  479.86   375.5  477.68   395.5   476.6
  400.89  477.65   407.5  480.02  415.51481.5437   435.4   488.7   455.4  494.74
   503.2  504.56     535  509.67   622.6  518.32   702.2  524.85   734.1   526.8
#Mann= 12 ,-1 , 0
       0    .016       0    9.46     .06       0   39.72     .12       0
  112.68     .06       0  163.51     .12       0  215.22     .06       0
   221.8     .12       0  284.07     .06       0  331.31     .12       0
   375.5    .045       0  400.89     .12       0  415.51     .06       0
Bank Sta=375.5,400.89
XS Rating Curve= 0 ,0
Exp/Cntr=0.3,0.1

Type RM Length L Ch R = 1 ,4122.7  ,313.8,319.2,320.6
XS GIS Cut Line= 3
     2380582.229       301972.97     2380701.766      301330.177
     2381004.104       301222.97
#Sta/Elev= 30
       0  544.19    83.7  540.29  100.73537.2574   123.6  535.02   139.5   530.6
   151.5  530.19   175.4  525.88   334.9  491.74   382.7  483.61   434.6  479.82
   444.6  477.88   450.5  477.21   466.4  478.11   482.4  479.31   510.3  477.79
   534.2  480.33   546.2  484.21   574.1  503.41     590  512.09  598.08518.4786
     606  522.59     614  523.96   760.7  535.36   780.5  538.16   796.4  542.01
   847.9  557.83  885.17566.8041   927.1  575.13   942.9  576.07   974.6   575.5
#Mann= 6 ,-1 , 0
       0     .06       0  100.73     .12       0   444.6    .045       0
   466.4     .12       0  598.08     .06       0  885.17     .12       0
Bank Sta=444.6,466.4
XS Rating Curve= 0 ,0
Exp/Cntr=0.3,0.1

Type RM Length L Ch R = 1 ,3803.4  ,299.8,304.7,261.8
XS GIS Cut Line= 3
      2380793.68      302012.871     2380931.297      301629.349
     2381122.714      301247.149
#Sta/Elev= 30
       0  512.83   19.65511.6784    32.7512.7775    43.9   513.6    55.9  513.03
    71.9  503.96   115.8  498.82   159.8  499.69   183.8  498.87   267.6  487.93
   331.6  482.04   387.5  479.35   407.5  477.19   415.4  476.74   427.4  476.94
   447.4  478.92   503.3  478.23   519.3  479.44   527.3  481.59   535.3  486.58
   547.3  496.34   555.3  501.59   607.2  532.37   655.2   562.8   671.1  570.36
   691.1  576.92   719.1  583.17     755  587.31     799  587.48   834.9  585.26
#Mann= 5 ,-1 , 0
       0     .12       0   19.65     .08       0    32.7     .12       0
   407.5    .045       0   427.4     .12       0
Bank Sta=407.5,427.4
XS Rating Curve= 0 ,0
Exp/Cntr=0.3,0.1

Type RM Length L Ch R = 1 ,3498.7  ,256.2,257.3,293.2
XS GIS Cut Line= 4
     2381077.747      302032.919     2381120.282      301801.148
     2381220.108      301502.537     2381240.942      301279.447
#Sta/Elev= 30
       0  539.62      16  536.93    63.9  525.18    75.9  521.02   119.8   509.4
   143.8  501.81   199.7  487.75   243.6  481.17   279.5  479.68   307.4  477.14
   309.6477.1877   324.6477.4297     423  478.55   430.9  480.07   438.9  484.07
   450.9  492.06   470.8  502.28   510.6  520.96   550.5  537.85   558.4  539.38
   566.2  539.68   585.9  534.91   589.8  536.29   601.6  544.82   629.1  555.08
   668.4  567.47   727.4  582.14   743.1  587.73   754.9  588.88   774.6  589.22
#Mann= 3 ,-1 , 0
       0     .12       0   309.6    .045       0   324.6     .12       0
Bank Sta=309.6,324.6
XS Rating Curve= 0 ,0
Exp/Cntr=0.3,0.1

Type RM Length L Ch R = 1 ,3241.3  ,364.1,381.7,398.8
XS GIS Cut Line= 3
     2381300.111      302117.935     2381400.805      301628.352
     2381515.389      301385.296
#Sta/Elev= 30
       0  543.16   63.12532.4052     104  525.08   154.9513.8538  209.63501.6208
   247.9  495.15   267.9  491.33   279.9  488.07   287.9  487.18   291.9  486.28
   303.9     482   323.9  476.99   339.9  477.01  387.41476.8349   387.9  476.83
  429.62477.3753   451.8     478   467.8   479.1   475.8  481.16   483.8   484.5
   527.5  508.24   574.9  535.33   598.6  550.71   614.4   559.7   630.2  567.54
     646  573.41   661.8  577.09   681.6  579.58   713.2  581.33   768.5  581.73
#Mann= 8 ,-1 , 0
       0     .06       0   63.12     .12       0   154.9     .06       0
  209.63     .12       0   323.9    .045       0   339.9     .12       0
  387.41     .06       0  429.62     .12       0
Bank Sta=323.9,339.9
XS Rating Curve= 0 ,0
Exp/Cntr=0.3,0.1

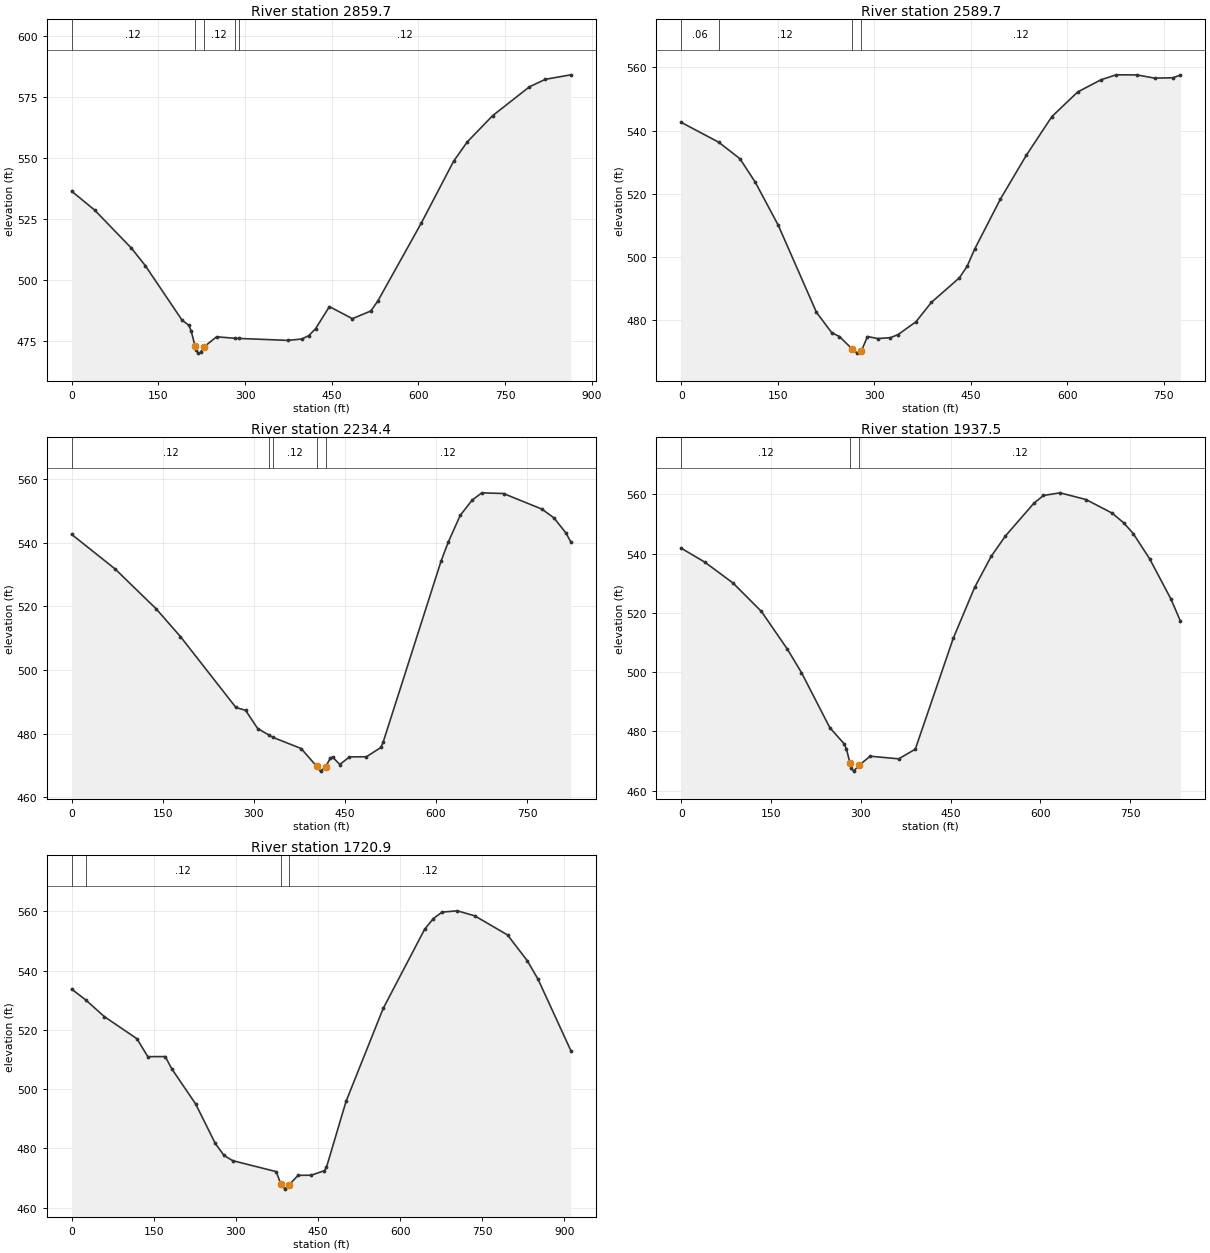
Type RM Length L Ch R = 1 ,2859.7  ,266.6,270,265.4
XS GIS Cut Line= 3
     2381373.028       302142.24     2381676.847      301815.852
     2381605.667      301404.393
#Sta/Elev= 30
       0  536.38    39.8  528.67   103.5  513.08   127.4  505.98   191.1  483.65
     203  481.55     207  479.11   213.5  473.03     215  471.63     219   470.2
     223   470.5   228.5  472.65   250.8  476.88  281.93476.2777  289.85476.1981
   374.2  475.41   398.1  475.97   410.1  477.34     422  480.18   445.9  489.22
   485.7  484.28   517.5  487.42   529.4  491.38     605   523.4   660.7  548.59
   684.5  556.54   728.3  567.24   791.9  579.03   819.7  582.11   863.5  583.93
#Mann= 5 ,-1 , 0
       0     .12       0   213.5    .045       0   228.5     .12       0
  281.93     .06       0  289.85     .12       0
Bank Sta=213.5,228.5
XS Rating Curve= 0 ,0
Exp/Cntr=0.3,0.1

Type RM Length L Ch R = 1 ,2589.7  ,368.2,355.2,335.9
XS GIS Cut Line= 3
     2381548.592      302301.095     2381829.842       301972.97
     2381956.578      301653.525
#Sta/Elev= 30
       0  542.61   57.93536.3662    91.2   531.1     115  523.67   150.7  510.05
   210.1  482.48   233.9  476.01   245.8  474.82   264.8  471.02   273.6  469.56
   279.8  470.23   289.4  474.82   305.3  474.17   325.1  474.46     337  475.44
   364.8   479.5   388.6  485.61   432.2   493.4   444.2  497.04   456.1  502.55
   496.1  518.39   536.1  532.15     576  544.46     616  552.23     652  556.08
   675.9  557.67   707.9  557.65   735.9  556.62   763.8  556.74   775.8  557.57
#Mann= 4 ,-1 , 0
       0     .06       0   57.93     .12       0   264.8    .045       0
   279.8     .12       0
Bank Sta=264.8,279.8
XS Rating Curve= 0 ,0
Exp/Cntr=0.3,0.1

Type RM Length L Ch R = 1 ,2234.4  ,277.8,296.9,323.2
XS GIS Cut Line= 3
     2381827.889      302623.143     2382021.954      302143.603
     2382175.111      301880.088
#Sta/Elev= 30
       0  542.58    71.6  531.72   139.3  519.18   179.1  510.51   270.6  488.22
   286.5  487.34   306.4  481.61  325.59479.5047  330.89478.8969     378  475.34
   403.3  469.81   409.9  468.24   418.3  469.56   425.8  472.26   429.8  472.67
   441.7  470.32   457.6  472.71   485.5  472.75   509.4  475.68   513.3  477.48
   608.4  534.15   620.2   540.1     640  548.55   659.8  553.36   675.6  555.62
   711.3   555.4   774.6   550.5   794.4  547.76   814.2  542.98   822.1  540.22
#Mann= 5 ,-1 , 0
       0     .12       0  325.59     .06       0  330.89     .12       0
   403.3    .045       0   418.3     .12       0
Bank Sta=403.3,418.3
XS Rating Curve= 0 ,0
Exp/Cntr=0.3,0.1

Type RM Length L Ch R = 1 ,1937.5  ,227.7,216.6,202.1
XS GIS Cut Line= 4
      2381867.44      302654.888     2382032.371      302496.902
     2382348.029      302270.098     2382417.788       302064.61
#Sta/Elev= 30
       0  541.79    39.4  537.09    86.6  530.03   133.9  520.46   177.2  507.76
   200.8  499.85   248.2  481.24     272  475.84     276     474     282  469.25
   283.9  467.68   287.9  466.58     297  468.54   315.6  471.62   363.2  470.73
     391  473.98   454.5  511.43   490.2  528.59   517.9  539.07   541.7  545.95
   589.3     557   605.2  559.59   632.9  560.49   676.3  558.22   719.7  553.67
   739.4  550.34   755.2  546.74   782.8  538.16   818.3  524.61   834.1  517.17
#Mann= 3 ,-1 , 0
       0     .12       0     282    .045       0     297     .12       0
Bank Sta=282,297
XS Rating Curve= 0 ,0
Exp/Cntr=0.3,0.1

Type RM Length L Ch R = 1 ,1720.9  ,371.2,347.5,337.3
XS GIS Cut Line= 3
     2382078.529      302906.896     2382252.779      302558.397
     2382440.478      302071.233
#Sta/Elev= 30
       0  533.77   25.89  530.11    59.6  524.52   119.3  517.03   139.2  510.98
     171  511.02   182.9  506.88   226.6  495.01   262.4   481.7   278.3  477.66
   294.2  475.89   373.7   472.2   382.1  468.02   389.6  466.29   397.1  467.72
   413.6  470.94   437.5  470.98   461.4  472.49   465.4  473.62   501.2  495.89
     569  527.24   644.7  553.95   660.6  557.57   676.6  559.76   704.5  560.19
   736.4  558.49   796.1  552.06     832  543.42   851.9  537.12   911.7  513.06
#Mann= 4 ,-1 , 0
       0     .06       0   25.89     .12       0   382.1    .045       0
   397.1     .12       0
Bank Sta=382.1,397.1
XS Rating Curve= 0 ,0
Exp/Cntr=0.3,0.1