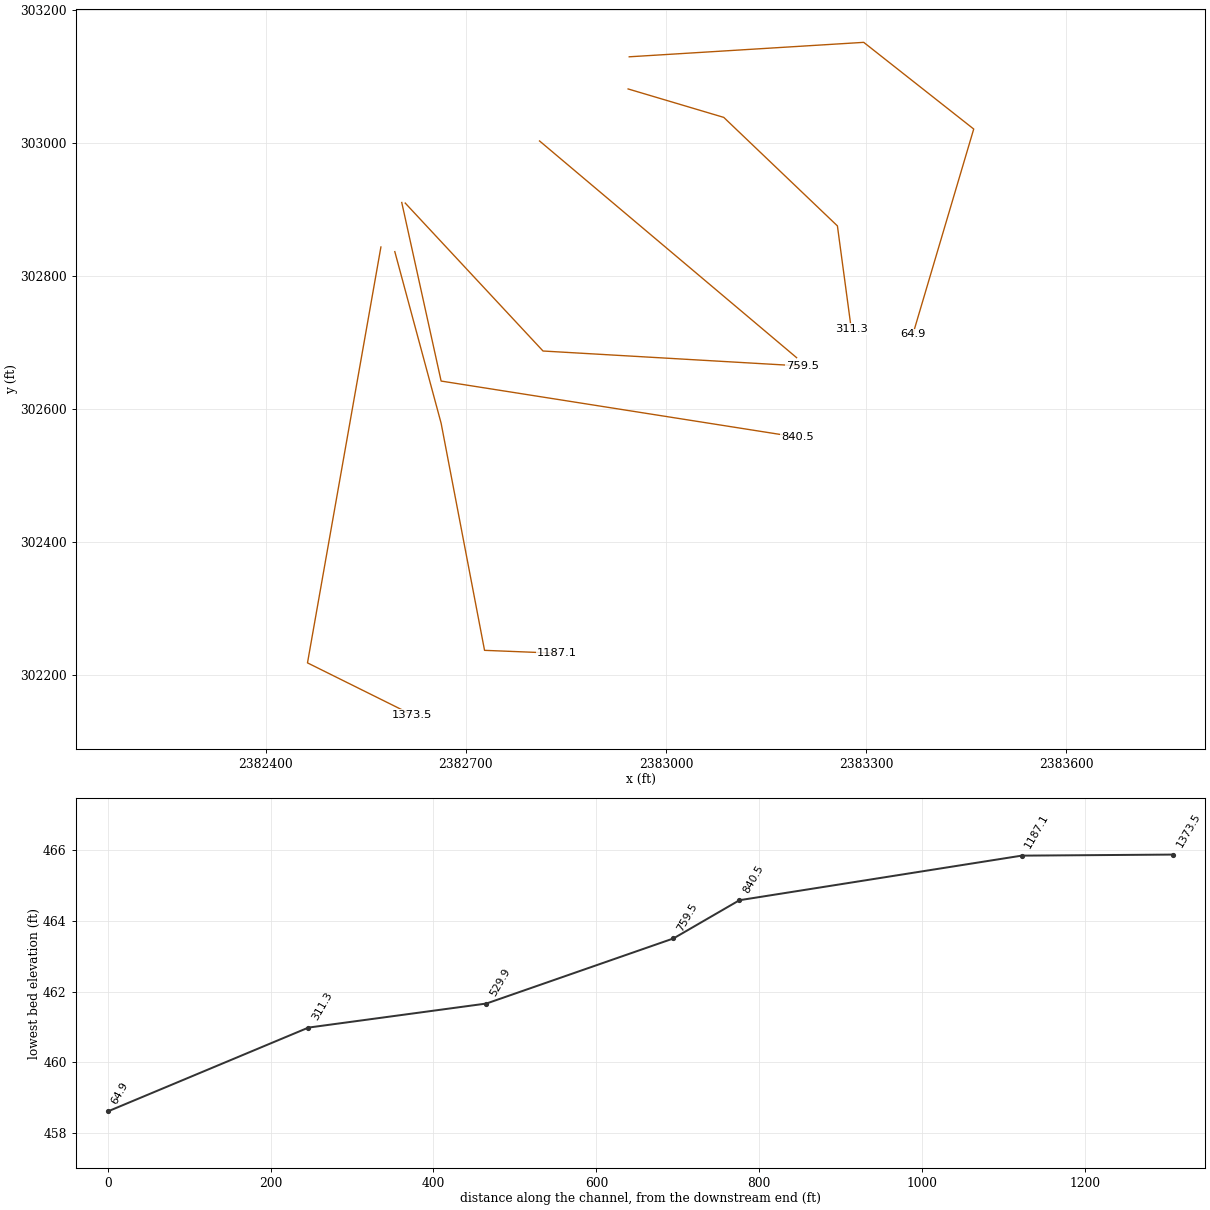
HEC-RAS study SYLVANRUN.prj: SYLVANRUN

--- SYLVANRUN.g01 (geometry) --- (continued)

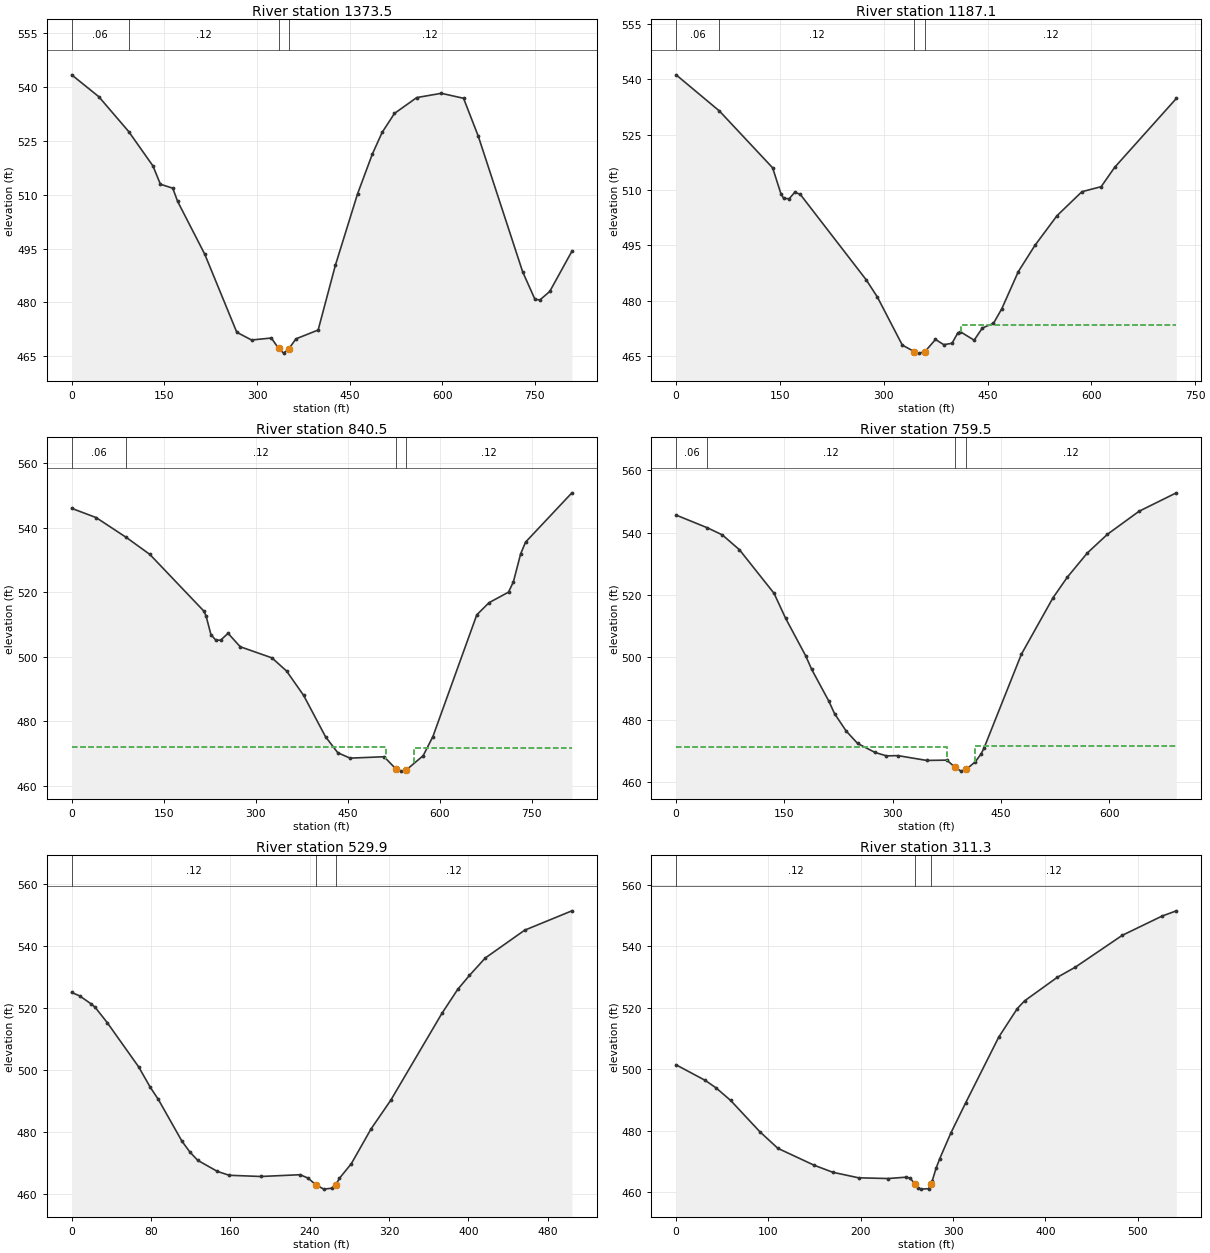
Type RM Length L Ch R = 1 ,1373.5  ,174.5,186.4,195.8
XS GIS Cut Line= 3
     2382572.525      302843.361     2382462.437      302218.629
     2382619.555      302140.504
#Sta/Elev= 30
       0  543.43    43.9  537.34   92.32527.6187   131.7  518.01   143.6  512.94
   163.6  511.84   171.6  508.13   215.4  493.45   267.3  471.68   291.2  469.53
   323.2  470.08   335.1  467.18   343.1  465.87   351.1  466.99   363.1  469.85
     399  472.31   426.9  490.36   462.8  510.26   486.7  521.33   502.7  527.42
   522.6  532.68   558.6  537.09   598.4  538.28   634.4  536.89   658.3   526.3
   730.1  488.52     750  480.86     758   480.7   773.9  483.05   809.8  494.27
#Mann= 4 ,-1 , 0
       0     .06       0   92.32     .12       0   335.1    .045       0
   351.1     .12       0
Bank Sta=335.1,351.1
XS Rating Curve= 0 ,0
Exp/Cntr=0.3,0.1

Type RM Length L Ch R = 1 ,1187.1  ,316.8,346.6,375.6
XS GIS Cut Line= 4
     2382593.358      302836.417     2382662.803      302578.604
     2382727.907      302237.458     2382836.414      302233.118
#Sta/Elev= 30
       0  541.16   62.56 531.377   139.5  515.99   151.4  509.01   155.4  507.74
   163.4  507.62   171.4  509.37   179.3  508.84     275  485.61     291  480.97
   326.9  468.01   344.3  466.24   350.8  465.84   359.3  466.18   374.8  469.54
   386.8  468.13   398.7   468.5   406.7  471.18   410.7  471.64   430.7  469.34
   442.6  472.65   458.6   473.9   470.6  477.83   494.5  487.89   518.5  494.99
   550.4  503.03   586.4  509.52   614.3   510.9   633.7  516.11   722.9  534.77
#Mann= 4 ,-1 , 0
       0     .06       0   62.56     .12       0   344.3    .045       0
   359.3     .12       0
#XS Ineff= 2 , 0
                          411.15          473.51
Permanent Ineff=
       F       F
Bank Sta=344.3,359.3
XS Rating Curve= 0 ,0
Exp/Cntr=0.3,0.1

Type RM Length L Ch R = 1 ,840.5   ,80,81,83
XS GIS Cut Line= 3
     2382603.775      302910.201     2382662.803      302641.972
     2383196.657      302557.771
#Sta/Elev= 30
       0  546.06    39.8   543.2   89.12537.0286   127.4  531.77   214.9   514.3
   218.9  512.73   226.9  506.93   234.8  505.19   242.8  505.19   254.8  507.32
   274.6  503.15   326.3   499.7   350.2  495.61     378  488.05   413.7  475.22
   433.6  470.29   453.5  468.61   509.1  469.04     529  465.12   536.9  464.58
   544.9   464.9   572.7  469.36   588.6   475.3   660.1  513.04     680   516.8
   711.8  520.08   719.7  523.24   731.6  531.96   739.6  535.59   815.1  550.87
#Mann= 4 ,-1 , 0
       0     .06       0   89.12     .12       0     529    .045       0
   544.9     .12       0
#XS Ineff= 2 , 0
          511.87  471.99  558.31          471.82
Permanent Ineff=
       F       F
Bank Sta=529,544.9
XS Rating Curve= 0 ,0
Exp/Cntr=0.3,0.1

Type RM Length L Ch R = 1 ,759.5   ,244.8,229.7,213.2
XS GIS Cut Line= 3
     2382608.983      302909.333     2382815.581      302687.111
      2383204.47      302664.542
#Sta/Elev= 30
       0  545.64   43.09541.5872    63.9   539.3    87.8  534.51   135.7  520.53
   151.7  512.54   179.7  500.41   187.6  496.24   211.6  485.94   219.6   481.9
   235.6  476.37   251.5  472.37   275.5   469.5   291.4   468.4   307.4  468.47
   347.2  466.93     375  467.03   386.7   464.7   394.8   463.5   401.7  464.03
   414.7  466.54   422.7  469.11   426.6  470.92   478.3  500.99     522  519.06
   541.9   525.7   569.7  533.49   597.6  539.49   641.3  546.86     693  552.78
#Mann= 4 ,-1 , 0
       0     .06       0   43.09     .12       0   386.7    .045       0
   401.7     .12       0
#XS Ineff= 2 , 0
          375.64  471.32  414.65          471.49
Permanent Ineff=
       F       F
Bank Sta=386.7,401.7
XS Rating Curve= 0 ,0
Exp/Cntr=0.3,0.1

Type RM Length L Ch R = 1 ,529.9   ,221.1,218.6,216.3
XS GIS Cut Line= 2
     2382810.372      303002.649     2383195.789      302677.128
#Sta/Elev= 30
       0  524.97     7.9  523.89    19.9  521.23    23.8  520.14    35.8  515.29
    67.5  501.04    79.4  494.38    87.4  490.54   111.2   477.1   119.2  473.61
   127.1  470.94     147  467.36   158.9  466.12   190.7  465.73   230.4   466.3
   238.3  465.22   246.3  463.06   254.2  461.66   262.2  461.95   266.2     463
   270.1  465.17     282  469.84   301.9  481.03   321.8  490.28   373.4  518.24
   389.3  525.95   401.2  530.47   417.1  536.06   456.8  545.01   504.5  551.25
#Mann= 3 ,-1 , 0
       0     .12       0   246.3    .045       0   266.2     .12       0
Bank Sta=246.3,266.2
XS Rating Curve= 0 ,0
Exp/Cntr=0.3,0.1

Type RM Length L Ch R = 1 ,311.3   ,244.3,246.4,249.3
XS GIS Cut Line= 4
     2382943.185      303080.774     2383086.569      303038.074
     2383256.987      302875.045      2383277.82      302720.097
#Sta/Elev= 30
       0  501.45    31.5   496.4    43.3  493.94    59.1  489.85    90.6   479.7
   110.2  474.27   149.6  468.75   169.6  466.48   197.6  464.67   229.6  464.43
   249.5  464.88   253.5  464.54     259  462.54   261.5  461.41   265.5  460.98
   273.5  461.12  275.69462.5654   277.5  463.76   281.5  467.72   285.5  470.88
   297.5  479.21   313.5  489.01   349.5  510.51   369.5  519.76   377.4  522.28
   412.8  529.94   432.4  533.26   483.2  543.62   526.2  549.87   541.8   551.6
#Mann= 3 ,-1 , 0
       0     .12       0     259    .045       0  275.69     .12       0
Bank Sta=259,275.69
XS Rating Curve= 0 ,0
Exp/Cntr=0.3,0.1

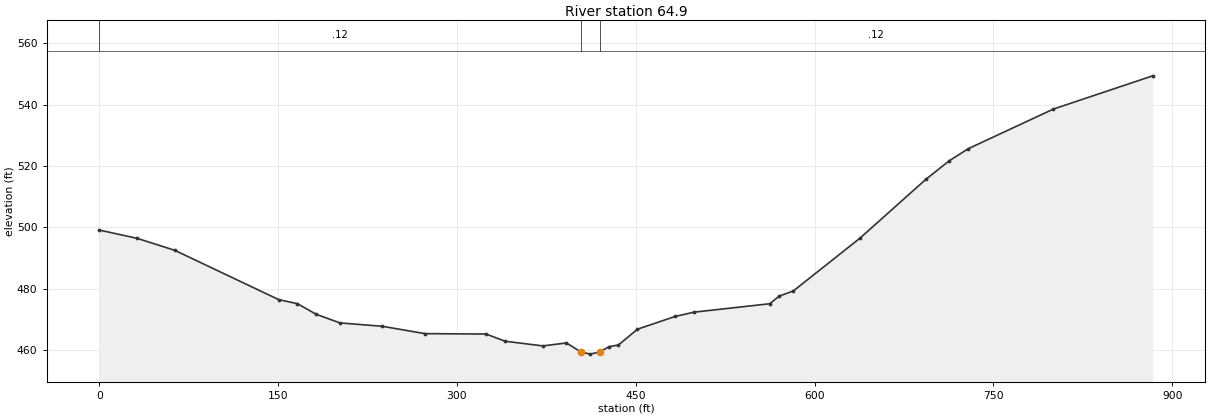
Type RM Length L Ch R = 1 ,64.9    ,79.2,64.9,49.2
XS GIS Cut Line= 4
      2382944.87      303129.074     2383296.433      303150.776
     2383461.363      303020.567     2383370.218      302712.408
#Sta/Elev= 30
       0  499.09    31.7  496.39    63.3  492.48   150.4  476.41   166.2  475.06
     182   471.6   201.8   468.8   237.5  467.69   273.1   465.3   324.5  465.16
   340.4  462.82   372.1  461.29   391.9  462.26   403.8  459.36   411.7  458.61
   419.6   459.3   427.6  461.04   435.5   461.6   451.4  466.74   483.1  470.91
   498.9  472.31   562.4  475.05   570.3  477.53   582.2  479.23   637.8  496.35
   693.3  515.62   713.1  521.72     729  525.65   800.4  538.58   883.7  549.42
#Mann= 3 ,-1 , 0
       0     .12       0   403.8    .045       0   419.6     .12       0
Bank Sta=403.8,419.6
XS Rating Curve= 0 ,0
Exp/Cntr=0.3,0.1
LCMann Table=0

Chan Stop Cuts=-1
Use User Specified Reach Order=0
Composite Channel Slope=5